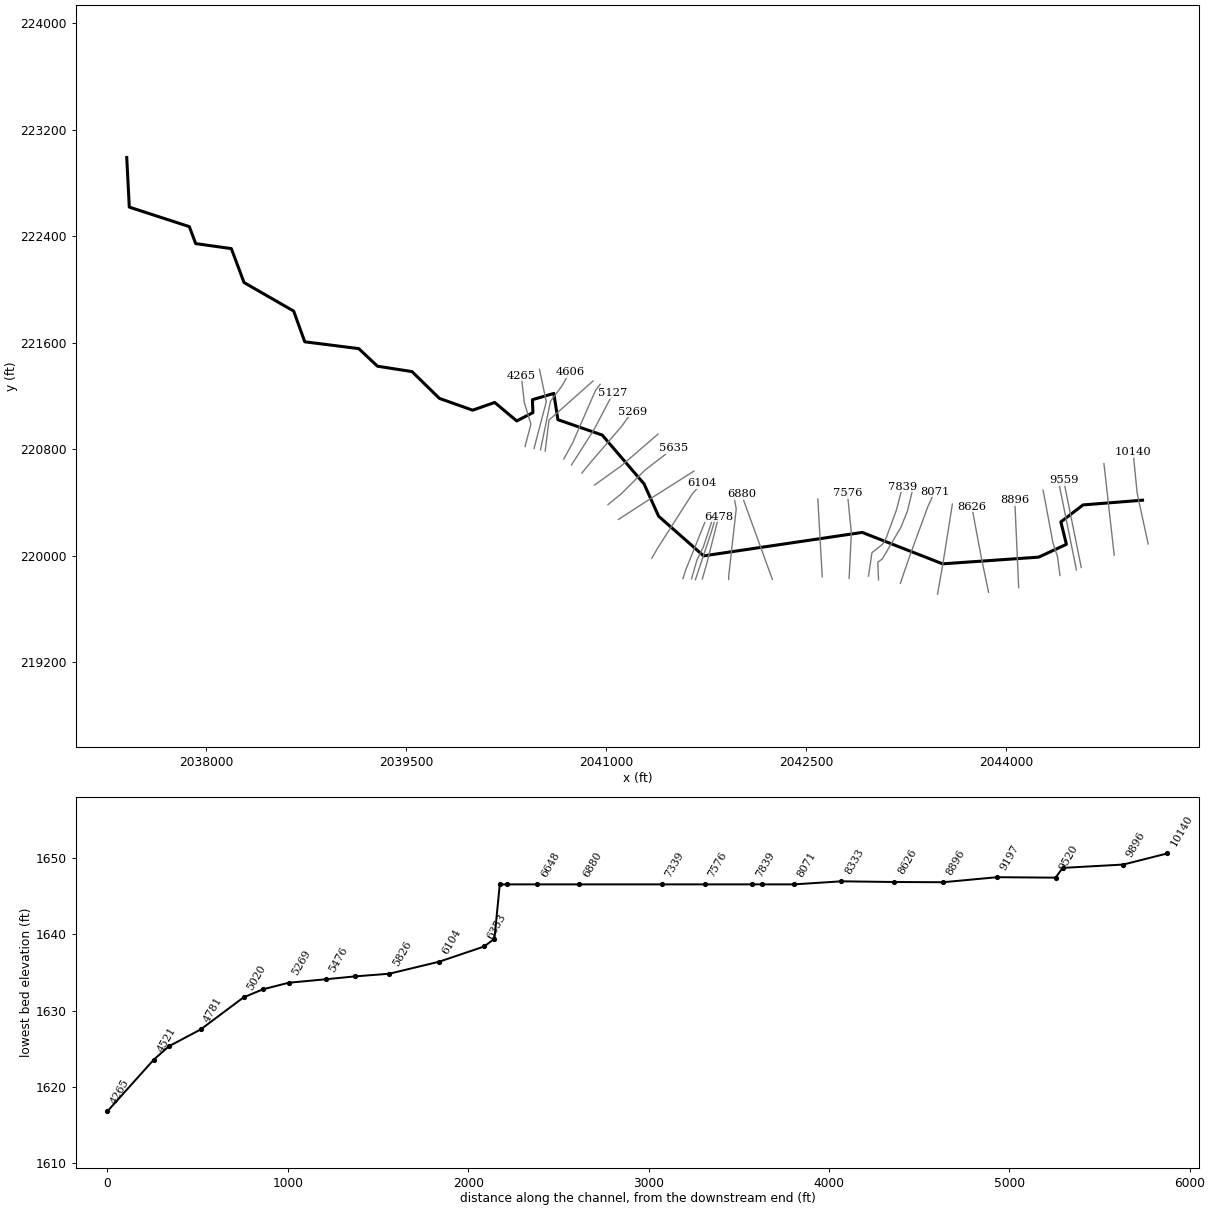
--- STONYCK.prj (project) ---

Proj Title=STONYCK
Current Plan=p01
Default Exp/Contr=0,0
English Units
Geom File=g01
Flow File=f01
Plan File=p01
Background Map Layer=Inundation Boundary (01pct Value_0)
BEGIN DESCRIPTION:
Stream Name: Stony Creek
Flood Zone: Approximate
Summers County, West Virginia
HEC-RAS Version: 5.0.7
Hydrology Method:
Regression.
Model Notes:
END DESCRIPTION:
DSS Export Rating Curves= 0
DSS Export Rating Curve Sorted= 0
DSS Export Volume Flow Curves= 0
DXF OffsetX= 0
DXF OffsetY= 0
DXF ScaleX= 0
DXF ScaleY= 0

--- STONYCK.p01 (plan) ---

Plan Title=Floodplain
Program Version=5.07
Short Identifier=Floodplain
Geom File=g01
Flow File=f01
Subcritical Flow
K Sum by GR= 0
Std Step Tol= 0.01
Critical Tol= 0.01
Num of Std Step Trials= 20
Max Error Tol= 0.3
Flow Tol Ratio= 0.001
Split Flow NTrial= 30
Split Flow Tol= 0.02
Split Flow Ratio= 0.02
Log Output Level= 0
Friction Slope Method= 1
Unsteady Friction Slope Method= 2
Unsteady Bridges Friction Slope Method= 1
Parabolic Critical Depth
Global Vel Dist= 0 , 0 , 0
Global Log Level= 0
CheckData=True
Encroach Param=-1 ,0,0, 0
Mapping Interval=1HOUR
Computation Time Step Use Courant=        0
Computation Time Step Use Time Series=    0
Computation Time Step Count To Double=0
Computation Time Step Max Doubling=0
Computation Time Step Max Halving=0
Computation Time Step Residence Courant=0
Run HTab= 0
Run UNet= 0
Run Sediment= 0
Run PostProcess= 0
Run WQNet= 0
Run RASMapper= 0
UNET Theta= 0
UNET Theta Warmup= 0
UNET ZTol= 0
UNET ZSATol= 0
UNET MxIter= 0
UNET Max Iter WO Improvement= 0
UNET MaxInSteps= 0
UNET DtIC= 0
UNET DtMin= 0
UNET MaxCRTS= 0
UNET WFStab= 0
UNET SFStab= 0
UNET WFX= 1
UNET SFX= 1
UNET 1D Methodology=Finite Difference
UNET DSS MLevel= 1
UNET Pardiso=0
UNET DZMax Abort= 0
UNET Use Existing IB Tables= 0
UNET Froude Reduction=False
UNET Froude Limit= 0
UNET Froude Power= 0
UNET D1 Cores= 0
UNET D2 Coriolis=0
UNET D2 Cores= 0
UNET D2 Theta= 1
UNET D2 Theta Warmup= 1
UNET D2 Z Tol= 0.01
UNET D2 Volume Tol= 0.01
UNET D2 Max Iterations= 20
UNET D2 Equation= 0
UNET D2 RampUpFraction=0.1
UNET D2 TimeSlices= 1
UNET D2 BCVolumeCheck=0
UNET D1D2 MaxIter= 0
UNET D1D2 ZTol=0.01
UNET D1D2 QTol=0.1
UNET D1D2 MinQTol=1
Write IC File= 0
Write IC File at Fixed DateTime=0
Write IC File at Sim End=0
Echo Input=False
Echo Parameters=False
Echo Output=False
Write Detailed= 0
HDF Write Warmup=0
HDF Write Time Slices=0
HDF Flush=0
HDF Face Node Velocities=0
HDF Compression= 1
HDF Chunk Size= 1
HDF Spatial Parts= 1
HDF Use Max Rows=0
HDF Fixed Rows= 1
Calibration Method= 0
Calibration Iterations= 20
Calibration Max Change=0.05
Calibration Tolerance=0.2
Calibration Maximum=1.5
Calibration Minimum=0.5
Calibration Optimization Method= 1
WQ AD Non Conservative
WQ ULTIMATE=-1
WQ Max Comp Step=1HOUR
WQ Output Interval=15MIN
WQ Output Selected Increments= 0
WQ Output face flow=0
WQ Output face velocity=0
WQ Output face area=0
WQ Output face dispersion=0
WQ Output cell volume=0
WQ Output cell surface area=0
WQ Output cell continuity=0
WQ Output cumulative cell continuity=0
WQ Output face conc=0
WQ Output face dconc_dx=0
WQ Output face courant=0
WQ Output face peclet=0
WQ Output face adv mass=0
WQ Output face disp mass=0
WQ Output cell mass=0
WQ Output cell source sink temp=0
WQ Output nsm pathways=0
WQ Output nsm derived pathways=0
WQ Output MaxMinRange=-1
WQ Daily Max Min Mean=-1
WQ Daily Range=0
WQ Daily Time=0
WQ Create Restart=0
WQ Fixed Restart=0
WQ System Summary=0
WQ Write To DSS=0
WQ Use Fixed Temperature=0
Sorting and Armoring Iterations= 10
XS Update Threshold= 0.02
Bed Roughness Predictor= 0
Hydraulics Update Threshold= 0.02
Energy Slope Method= 1
Volume Change Method= 1
Sediment Retention Method= 0
XS Weighting Method= 0
Number of US Weighted Cross Sections= 1
Number of DS Weighted Cross Sections= 1
Upstream XS Weight=0
Main XS Weight=1
Downstream XS Weight=0
Number of DS XS's Weighted with US Boundary= 1
Upstream Boundary Weight= 1
Weight of XSs Associated with US Boundary= 0
Number of US XS's Weighted with DS Boundary= 1
Downstream Boundary Weight= 0.5
Weight of XSs Associated with DS Boundary= 0.5
Percentile Method= 0
Sediment Output Level= 3
Mass or Volume Output= 0
Output Increment Type= 1
Profile and TS Output Increment= 1
XS Output Flag= 0
XS Output Increment= 10
Write Gradation File= 0
Read Gradation Hotstart= 0
Write HDF5 File= 1
Write Binary Output= 1
Write DSS Sediment File= 0
SV Curve= 0
Specific Gage Flag= 0

--- STONYCK.f01 (steady flow) ---

Flow Title=Flows
Program Version=5.07
Number of Profiles= 6
Profile Names=01pct,10pct,04pct,02pct,0_2pct,01plus
River Rch & RM=STONYCK,Main            ,10140
    1200     653     856    1020    1650    1780
River Rch & RM=STONYCK,Main            ,7339
    1351     738     966    1152    1856    1998
Boundary for River Rch & Prof#=STONYCK,Main            , 1
Up Type= 0
Dn Type= 3
Dn Slope=0.02691
Boundary for River Rch & Prof#=STONYCK,Main            , 2
Up Type= 0
Dn Type= 3
Dn Slope=0.02691
Boundary for River Rch & Prof#=STONYCK,Main            , 3
Up Type= 0
Dn Type= 3
Dn Slope=0.02691
Boundary for River Rch & Prof#=STONYCK,Main            , 4
Up Type= 0
Dn Type= 3
Dn Slope=0.02691
Boundary for River Rch & Prof#=STONYCK,Main            , 5
Up Type= 0
Dn Type= 3
Dn Slope=0.02691
Boundary for River Rch & Prof#=STONYCK,Main            , 6
Up Type= 0
Dn Type= 3
Dn Slope=0.02691
DSS Import GetInterval= 0
DSS Import GetPeak= 0
DSS Import FillOption= 0

--- STONYCK.g01 (geometry) ---

Geom Title=Geometry
Program Version=5.07

River Reach=STONYCK         ,Main
Reach XY= 30
     2045025.365      220416.926     2044579.184      220381.336
     2044412.518      220253.732     2044454.184      220085.329
     2044245.851      219988.975     2043525.365      219938.627
     2042922.066      220174.739     2041731.962      219998.523
     2041394.289      220296.266     2041284.913      220539.322
     2040970.831      220906.356     2040638.212      221021.961
      2040607.83      221219.009      2040447.24      221172.134
     2040450.712      221074.912     2040329.184      221012.412
     2040164.254      221151.301     2039998.667      221093.304
     2039749.323      221181.683     2039543.594      221383.072
     2039284.045      221423.871     2039144.288      221555.815
     2038738.906       221607.03     2038655.573      221837.933
     2038283.177      222052.343     2038187.691      222307.551
      2037920.33      222344.878     2037872.587      222472.482
     2037422.066      222619.183     2037402.879      222991.936

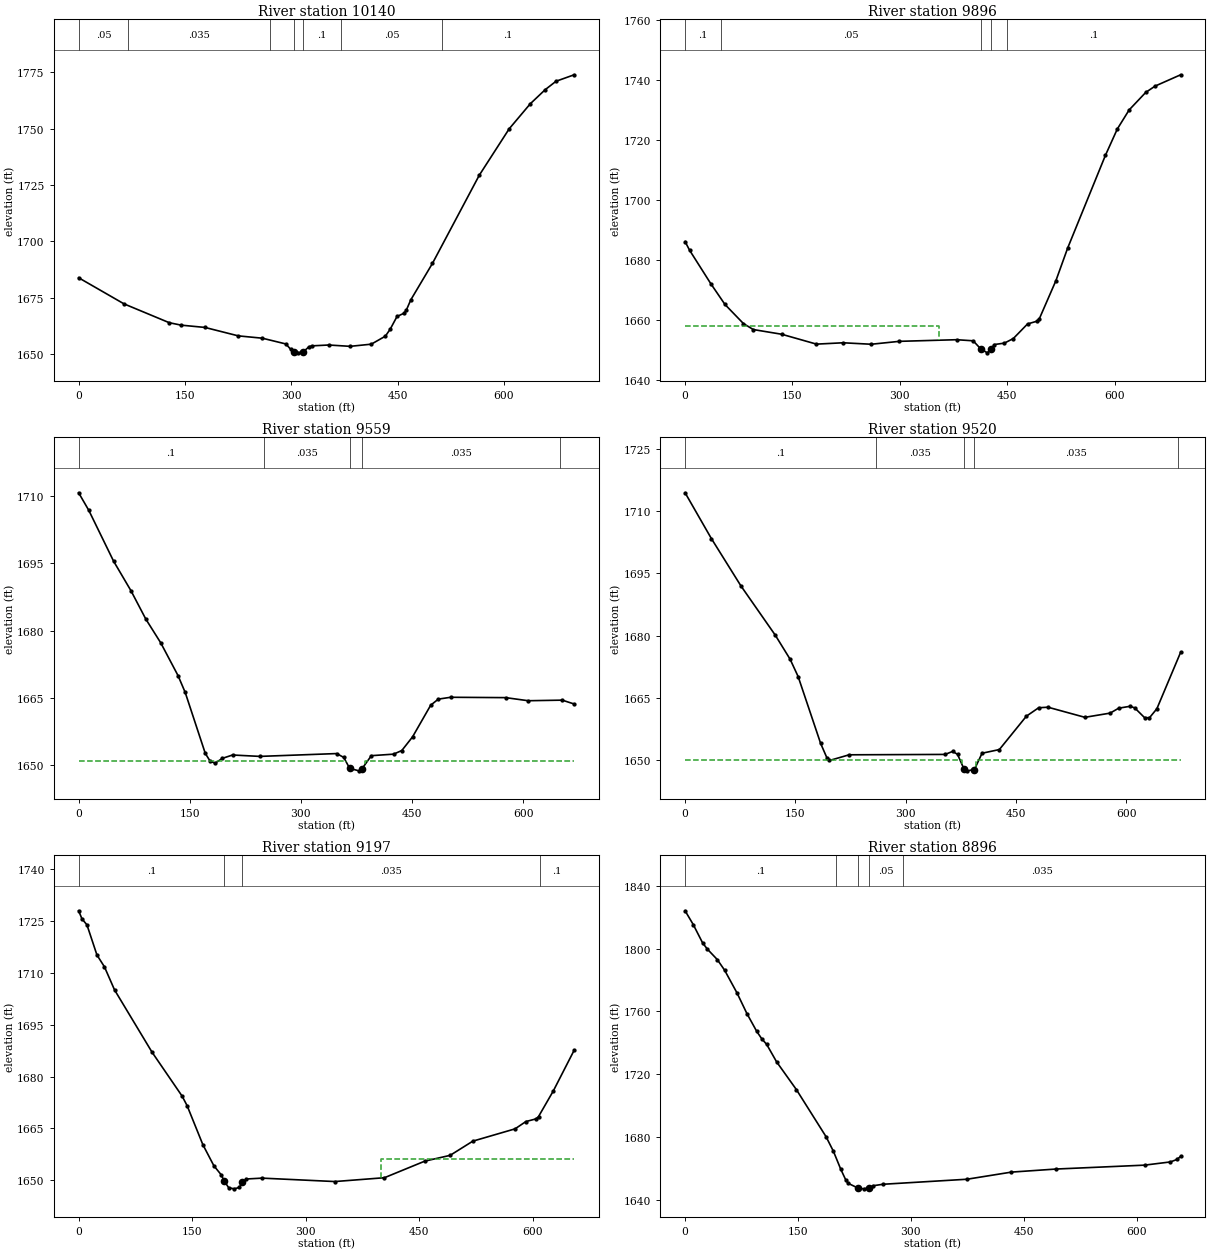
Type RM Length L Ch R = 1 ,10140   ,246.8,244.4,246.1
XS GIS Cut Line= 3
2045067.61748609220088.039712301     2044984.849      220471.573
2044954.82342059220776.717321459
#Sta/Elev= 30
       0  1683.9    64.1 1672.31   127.9 1663.97   144.7 1662.89   178.2 1661.88
   225.2 1658.14   259.1 1657.11   292.4 1654.55   299.1 1652.18   304.11651.186
   309.1 1650.62   317.11651.145   324.9  1653.3   329.3 1653.72   352.8 1654.09
     383  1653.5   412.8 1654.46   432.6 1657.99   439.4 1661.05   449.1 1666.73
     459 1668.18   462.3  1669.6   468.6 1674.13   499.1 1690.27   565.1 1729.32
   607.3  1749.9   637.1 1761.01   658.1 1767.25   673.4 1770.99     699 1773.86
#Mann= 7 ,-1 , 0
       0     .05       0      70    .035       0     270      .1       0
   304.1    .045       0   317.1      .1       0     370     .05       0
  512.36      .1       0
Bank Sta=304.1,317.1
XS Rating Curve= 0 ,0
Exp/Cntr(USF)=0,0
Exp/Cntr=0.3,0.1

Type RM Length L Ch R = 1 ,9896    ,333.7,336.5,336.7
XS GIS Cut Line= 2
2044812.89150072220003.5242749252044735.88271978220691.292690472
#Sta/Elev= 30
       0  1686.2     6.2 1683.35    35.9 1672.18    55.7 1665.26    81.5  1658.9
    95.3 1656.91   134.9 1655.35   183.5 1652.06   220.7 1652.51     260 1652.02
   299.3 1652.99   379.2 1653.53   402.3 1653.17   412.9 1650.48   422.1 1649.16
   427.9 1650.55     432 1651.93   445.9 1652.39   458.4 1653.92   478.3 1658.78
   491.5  1659.7   494.8 1660.54   517.9 1673.19   534.4  1684.1   587.1 1714.95
   603.7 1723.71   620.2 1730.04   643.3 1735.86   656.5 1737.98   692.1 1741.74
#Mann= 5 ,-1 , 0
       0      .1       0      50     .05       0   412.9    .045       0
   427.9     .05       0     450      .1       0
#XS Ineff= 2 , 0
             355    1658
Permanent Ineff=
       F       F
Bank Sta=412.9,427.9
XS Rating Curve= 0 ,0
Exp/Cntr(USF)=0,0
Exp/Cntr=0.5,0.3

Type RM Length L Ch R = 1 ,9559    ,39.2,39.2,39.2
XS GIS Cut Line= 2
2044565.57954465219910.9225233932044433.41557062220566.706746897
#Sta/Elev= 30
       0 1710.71    13.7  1706.8    47.2 1695.46    70.6 1688.89    90.7 1682.55
   110.8 1677.27   134.2 1669.95   143.9 1666.19     171  1652.6   177.7 1650.84
   184.4 1650.44     194  1651.5   207.8 1652.25   244.6 1651.94   348.4 1652.57
   357.9 1651.71     3661649.259   378.5 1648.72   382.41649.149   395.2  1652.1
   425.2 1652.44   436.3 1653.25   450.8 1656.29   475.3 1663.35   485.6 1664.71
   502.3 1665.12   576.5 1665.04     607 1664.35   652.9 1664.48     669 1663.62
#Mann= 5 ,-1 , 0
       0      .1       0     250    .035       0     366    .045       0
   382.4    .035       0     650      .1       0
#XS Ineff= 2 , 0
             361    1651     387            1651
Permanent Ineff=
       F       F
Bank Sta=366,382.4
XS Rating Curve= 0 ,0
Exp/Cntr(USF)=0,0
Exp/Cntr=0.5,0.3

Type RM Length L Ch R = 1 ,9520    ,321.8,323.6,316.1
XS GIS Cut Line= 2
2044529.32799342219892.6322637612044396.20188872220553.189897755
#Sta/Elev= 30
       0 1714.36    35.7 1703.35    75.9 1691.95   122.7 1680.07   142.8  1674.3
   153.7 1670.13   184.3 1654.04     193 1650.49   196.3 1649.93   223.1  1651.3
   353.6 1651.39   363.7 1652.11   370.4 1651.42   379.51647.769   383.8 1647.44
   393.4 1647.76   403.8 1651.68   427.3 1652.56   464.1  1660.6   480.8 1662.63
   493.5 1662.75   543.6 1660.32   577.9 1661.33   589.6 1662.52   604.9 1662.97
   611.3  1662.6   624.7 1660.25   631.4 1660.21   641.5 1662.39   673.8 1675.97
#Mann= 5 ,-1 , 0
       0      .1       0     260    .035       0   379.5    .045       0
   393.4    .035       0     670      .1       0
#XS Ineff= 2 , 0
             377    1650     395            1650
Permanent Ineff=
       F       F
Bank Sta=379.5,393.4
XS Rating Curve= 0 ,0
Exp/Cntr(USF)=0,0
Exp/Cntr=0.5,0.3

Type RM Length L Ch R = 1 ,9197    ,305.8,300.2,294.9
XS GIS Cut Line= 4
 2044406.0562437219851.1313960242044387.25308906219993.199675506
2044353.72924642220093.771203419 2044279.4598015220492.290176193
#Sta/Elev= 30
       0 1727.97     4.4 1725.64      11 1723.89    24.2 1715.17    34.1 1711.75
    47.4 1705.09      97 1687.04   136.7 1674.34   143.3 1671.58   164.1  1660.3
   178.7 1654.17   188.3 1651.58   192.5 1649.71   198.3 1647.81   205.6  1647.5
   212.5 1647.92   216.4 1649.42   221.7 1650.35   242.4  1650.6   338.5 1649.61
     404 1650.72   457.4 1655.52   490.8 1657.19   520.8  1661.3   576.6 1664.86
   590.9 1666.97   604.3 1667.75   607.6 1668.41   627.2 1675.86   654.7 1687.62
#Mann= 4 ,-1 , 0
       0      .1       0   192.5    .045       0   216.4    .035       0
  609.32      .1       0
#XS Ineff= 2 , 0
                             400            1656
Permanent Ineff=
       F       F
Bank Sta=192.5,216.4
XS Rating Curve= 0 ,0
Exp/Cntr(USF)=0,0
Exp/Cntr=0.3,0.1

Type RM Length L Ch R = 1 ,8896    ,266.5,269.9,271.8
XS GIS Cut Line= 2
 2044096.0061541219760.3102267342044066.66908292220417.953374444
#Sta/Elev= 30
       0 1824.18    10.8 1815.41    23.3 1803.66    29.6 1799.71    42.7  1793.1
    52.5 1786.28      69 1771.75    82.1 1758.63    95.2 1747.24   101.8 1742.56
   108.4 1738.96   121.5 1727.87   147.8 1710.16   187.2 1680.14     197 1670.83
   206.9 1659.23   213.5 1652.46   216.7 1650.35   229.41647.397   237.1 1646.84
   244.1 1647.42   249.7  1648.8   262.7 1649.75   374.4 1652.96   433.5 1657.51
   492.6 1659.46   610.4 1661.95   644.8 1664.01   653.5  1665.6   658.3 1667.55
#Mann= 5 ,-1 , 0
       0      .1       0     200     .05       0   229.4    .045       0
   244.1     .05       0     290    .035       0
Bank Sta=229.4,244.1
XS Rating Curve= 0 ,0
Exp/Cntr(USF)=0,0
Exp/Cntr=0.3,0.1

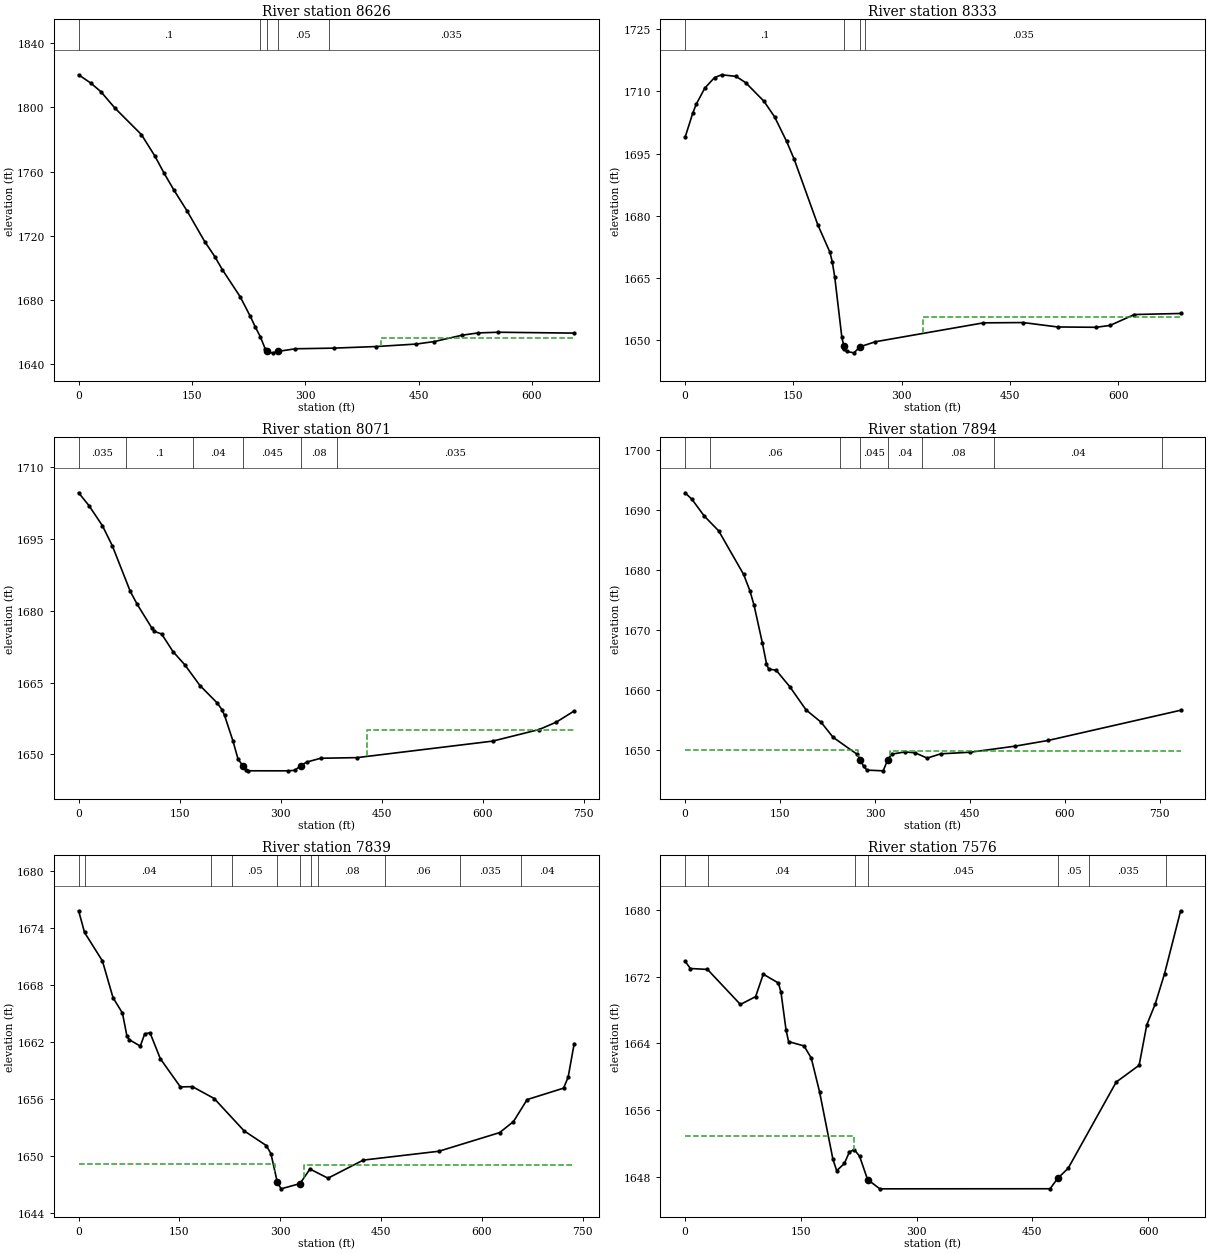
Type RM Length L Ch R = 1 ,8626    ,301,293.7,288.5
XS GIS Cut Line= 3
2043870.20455333219724.918605589     2043816.809      219980.245
 2043744.0568962220368.596628345
#Sta/Elev= 30
       0 1820.36      16 1815.21    29.4 1809.84    48.2  1799.5    83.1 1783.05
   100.9 1769.69   113.2  1758.9   125.8  1748.7   143.4 1735.52   166.9 1716.29
   180.3  1706.9   190.3 1698.73   213.8 1681.91   227.2 1669.69     234 1662.88
   240.6 1656.84   247.3    1649   249.61647.738   250.7 1647.15   257.4 1646.87
   264.1 1647.78     287 1649.41   337.6 1649.81   393.8  1650.8   447.2 1652.36
     471 1653.93   507.7 1657.88   528.7 1659.29   555.1 1659.72     656 1659.18
#Mann= 5 ,-1 , 0
       0      .1       0     240     .05       0   249.6    .045       0
   264.1     .05       0  330.85    .035       0
#XS Ineff= 2 , 0
                             400            1656
Permanent Ineff=
       F       F
Bank Sta=249.6,264.1
XS Rating Curve= 0 ,0
Exp/Cntr(USF)=0,0
Exp/Cntr=0.3,0.1

Type RM Length L Ch R = 1 ,8333    ,263.5,261.8,259.1
XS GIS Cut Line= 3
2043487.01432377219710.423523731     2043526.986      219936.206
2043598.56431228 220387.85339571
#Sta/Elev= 30
       0 1698.95    10.7  1704.8    15.3 1706.86    27.3  1710.8    40.8 1713.34
    50.7 1714.01    70.6 1713.62      84  1712.1   109.4  1707.6     124 1703.86
   140.6 1697.97   151.2 1693.62   183.9 1677.82   200.6 1671.25   203.9 1668.92
   207.3  1665.3   217.2 1650.69  220.11 1648.51   220.6 1647.86   223.9 1647.29
   233.9 1646.96   242.6 1648.44   263.8 1649.64   413.3 1654.19   468.4 1654.26
   516.2  1653.2   569.4 1653.12   588.8 1653.57   622.5  1656.2   686.6 1656.45
#Mann= 4 ,-1 , 0
       0      .1       0  220.11    .045       0   242.6      .1       0
  249.29    .035       0
#XS Ineff= 2 , 0
                          329.54         1655.59
Permanent Ineff=
       F       F
Bank Sta=220.11,242.6
XS Rating Curve= 0 ,0
Exp/Cntr(USF)=0,0
Exp/Cntr=0.3,0.1

Type RM Length L Ch R = 1 ,8071    ,180.8,176.7,172.7
XS GIS Cut Line= 4
2043207.97975294219791.6784408452043273.55786212219983.728617756
2043414.08238181220367.8289715772043465.60803903220480.248587329
#Sta/Elev= 30
       0 1704.67    15.4 1701.98    35.4 1697.77    50.1 1693.56    76.7 1684.05
      87 1681.35     109 1676.33   112.5  1675.7   123.2 1675.16   140.2 1671.46
   157.5 1668.74   180.1 1664.39   205.4 1660.79   213.1 1659.29   216.6 1658.15
   228.9 1652.89   236.6 1649.02   243.6 1647.64     248 1646.76   251.5 1646.57
   310.9 1646.56     321 1646.67   329.5 1647.62   338.7  1648.4   359.4 1649.19
   413.1 1649.32   614.6 1652.77   683.5 1655.19   709.1 1656.74   735.6 1659.07
#Mann= 6 ,-1 , 0
       0    .035       0      70      .1       0     170     .04       0
   243.6    .045       0   329.5     .08       0  382.94    .035       0
#XS Ineff= 2 , 0
                          428.19         1655.07
Permanent Ineff=
       F       F
Bank Sta=243.6,329.5
XS Rating Curve= 0 ,0
Exp/Cntr(USF)=0,0
Exp/Cntr=0.5,0.3

Type RM Length L Ch R = 1 ,7894    ,54.8,55.2,55.7
XS GIS Cut Line= 6
2043044.60742681219818.8548711442043038.54493076219950.830268517
2043072.57928038219975.1405182442043211.14770382220210.949940591
2043262.19922824 220337.363239172043308.54057015220531.003846441
#Sta/Elev= 30
       0 1692.92      11 1691.81    30.1 1689.06    53.1 1686.56    92.5  1679.3
   102.3 1676.61   108.9 1674.19     122 1667.92   128.6 1664.42   131.9 1663.53
   143.8 1663.34   165.6 1660.56   191.1 1656.72   214.8 1654.67   233.9 1652.14
     271 1649.38   277.1 1648.45   281.9 1647.31   287.4 1646.68   312.9 1646.56
   320.2  1648.4   326.2 1649.34   347.2 1649.71   363.4 1649.57   382.5 1648.68
   403.9  1649.4   449.9 1649.66   520.5 1650.66   573.3 1651.62   782.9 1656.66
#Mann= 8 ,-1 , 0
       0      .1       0      40     .06       0  243.94     .04       0
   277.1    .045       0   320.2     .04       0  373.94     .08       0
  487.45     .04       0  753.78    .035       0
#XS Ineff= 2 , 0
          273.83 1649.97  323.89         1649.88
Permanent Ineff=
       F       F
Bank Sta=277.1,320.2
XS Rating Curve= 0 ,0
Exp/Cntr(USF)=0,0
Exp/Cntr=0.5,0.3

Type RM Length L Ch R = 1 ,7839    ,252.8,262.5,335.6
XS GIS Cut Line= 6
2042969.18133847219846.6991545732042994.76185283220022.418536709
2043074.04092839220085.2480283082043102.31335241220134.959474668
2043178.59807464220343.0497524292043223.77263687220517.005416157
#Sta/Elev= 30
       0 1675.78     8.8  1673.5    35.4 1670.51    51.2 1666.64    65.2 1665.03
    71.8 1662.63    75.2 1662.24    91.7 1661.56    98.4 1662.85   106.2 1662.96
   121.6 1660.23   151.4 1657.27   169.3  1657.3   201.7 1656.05   246.1 1652.66
   279.2 1651.11   286.1 1650.26   295.6 1647.26   301.2 1646.56   329.3 1647.11
   344.2 1648.64     371 1647.68   423.5 1649.58     536 1650.51   626.4 1652.47
     647 1653.63   667.3 1655.94   721.5 1657.14   728.3 1658.28   737.3 1661.82
#Mann= 11 ,-1 , 0
       0    .035       0      10     .04       0  197.57     .06       0
  227.57     .05       0   295.6    .045       0   329.3     .05       0
  345.92     .04       0  355.92     .08       0  455.92     .06       0
  567.55    .035       0  657.55     .04       0
#XS Ineff= 2 , 0
          292.36 1649.15  334.59         1649.07
Permanent Ineff=
       F       F
Bank Sta=295.6,329.3
XS Rating Curve= 0 ,0
Exp/Cntr(USF)=0,0
Exp/Cntr=0.5,0.3

Type RM Length L Ch R = 1 ,7576    ,226.7,237.5,255.6
XS GIS Cut Line= 3
2042823.64705544219829.761866149     2042840.577      220173.173
2042810.61848402220470.040586829
#Sta/Elev= 30
       0 1673.83     6.9 1672.97      29 1672.86    71.7 1668.66    91.4  1669.6
   101.3 1672.29     121 1671.23   124.3  1670.1   130.8 1665.62   134.1 1664.21
   154.1 1663.69   163.5 1662.24   174.3 1658.17   191.6 1650.09   196.5 1648.73
   206.4  1649.6     213 1650.99   219.2 1651.27   226.1 1650.47   236.5 1647.67
   252.4 1646.56     473 1646.57   482.8 1647.81   496.4 1649.02   558.7 1659.36
   588.4 1661.37   598.3 1666.21   609.3 1668.73   621.3 1672.33   642.2 1679.89
#Mann= 7 ,-1 , 0
       0    .035       0      30     .04       0     220    .025       0
   236.5    .045       0   482.8     .05       0  523.83    .035       0
  623.83      .1       0
#XS Ineff= 2 , 0
          218.29 1652.95
Permanent Ineff=
       F       F
Bank Sta=236.5,482.8
XS Rating Curve= 0 ,0
Exp/Cntr(USF)=0,0
Exp/Cntr=0.3,0.1

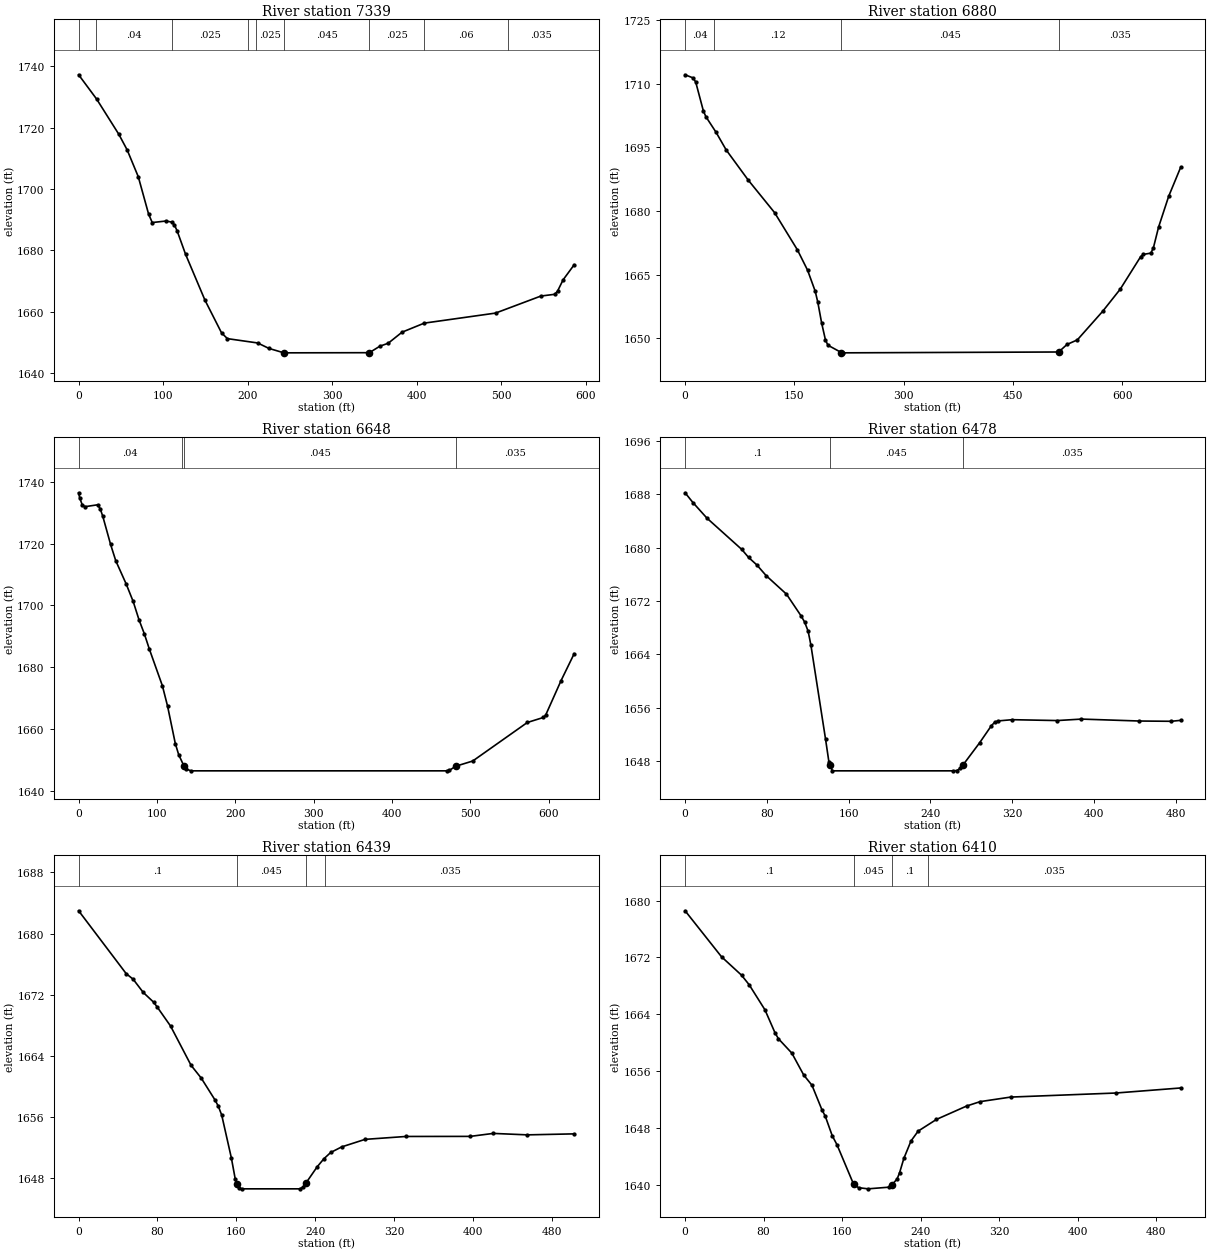
Type RM Length L Ch R = 1 ,7339    ,438.6,458.8,552.3
XS GIS Cut Line= 3
2042621.94509382219840.710157597     2042605.105       220138.57
2042588.84087626220426.251154899
#Sta/Elev= 30
       0 1737.24    21.3 1729.32    47.6 1717.82    57.5  1712.7    70.6 1703.99
    82.8 1691.82    87.1 1689.05   103.5 1689.55   110.1  1689.2   113.3 1688.33
   116.6 1686.32   126.6 1678.68   149.5 1663.75   169.2 1653.05   176.1 1651.19
   211.9 1649.78   225.1 1648.02   242.71646.579   244.5 1646.56   344.1 1646.61
   356.5 1648.72   366.4 1649.69   382.8  1653.3   409.1 1656.25   493.4 1659.52
   547.1 1665.08   563.5 1665.65   566.8 1666.67   573.4 1670.37   586.5 1675.28
#Mann= 9 ,-1 , 0
       0      .1       0      20     .04       0     110    .025       0
     200     .04       0     210    .025       0   242.7    .045       0
   344.1    .025       0  408.34     .06       0  508.34    .035       0
Bank Sta=242.7,344.1
XS Rating Curve= 0 ,0
Exp/Cntr(USF)=0,0
Exp/Cntr=0.3,0.1

Type RM Length L Ch R = 1 ,6880    ,255,232.2,100.5
XS GIS Cut Line= 2
2042247.57591085219822.0775341282042015.61314603220461.356258209
#Sta/Elev= 30
       0 1712.11    11.1 1711.36    14.6 1710.38      25 1703.64    28.5 1702.24
    42.5 1698.55    56.4 1694.39    86.8 1687.25   122.8 1679.62   154.2 1670.82
   168.1 1666.04   178.6 1661.07   182.1 1658.52   187.4 1653.59   192.6 1649.62
     196 1648.36   214.51646.624     217 1646.56   512.7 1646.76   524.1 1648.53
   538.3 1649.61     573 1656.33   597.2 1661.57   625.3 1669.25   628.8 1669.76
   639.3 1670.07   642.8 1671.37   649.8 1676.19   663.7 1683.47   680.1 1690.28
#Mann= 4 ,-1 , 0
       0     .04       0      40     .12       0   214.5    .045       0
   512.7    .035       0
Bank Sta=214.5,512.7
XS Rating Curve= 0 ,0
Exp/Cntr(USF)=0,0
Exp/Cntr=0.3,0.1

Type RM Length L Ch R = 1 ,6648    ,173.2,169.7,198.2
XS GIS Cut Line= 4
2041919.84820482219821.2911667442041919.74166582 219843.23140839
2041976.50262604220351.7150103442041958.89498152220449.011261382
#Sta/Elev= 30
       0 1736.39     1.3 1734.81     4.6 1732.48     7.9 1731.89    24.3 1732.51
    27.6 1731.19    30.9 1728.73    40.8  1719.7    47.4 1714.43    60.6 1706.98
    69.6 1701.29    77.1 1695.33    83.8 1690.88    90.4 1685.79   106.9 1674.05
   113.5 1667.48   123.4 1655.37   127.7 1651.79   134.31648.184   136.6 1647.25
   143.2 1646.56     470 1646.56   473.3 1646.72   481.11648.032     503 1649.73
   572.7 1662.18   593.3 1663.81   596.1 1664.56   615.8 1675.73   632.5 1684.41
#Mann= 4 ,-1 , 0
       0     .04       0  131.94     .12       0   134.3    .045       0
   481.1    .035       0
Bank Sta=134.3,481.1
XS Rating Curve= 0 ,0
Exp/Cntr(USF)=0,0
Exp/Cntr=0.3,0.1

Type RM Length L Ch R = 1 ,6478    ,41.3,38.9,84
XS GIS Cut Line= 4
 2041721.9611019219825.0600829642041755.99833505219943.057094198
2041805.66417525220139.3554149522041844.63332642220294.178655794
#Sta/Elev= 30
       0  1688.2     7.7 1686.73    21.4  1684.4    55.5 1679.71    62.1 1678.52
    70.1 1677.41    79.4 1675.78    99.2 1673.02   113.6 1669.74     117 1668.83
   120.4 1667.47   123.1 1665.39   137.4 1651.34   140.7 1647.91     142 1647.37
   144.1 1646.56   262.6 1646.56     266 1646.61   269.3 1646.94   271.6 1647.37
   288.1 1650.74   299.8 1653.34   303.2 1653.87   306.6 1654.04   320.1 1654.22
   364.1 1654.09   387.8 1654.31   444.6 1654.02   475.7 1653.98   484.9 1654.12
#Mann= 3 ,-1 , 0
       0      .1       0     142    .045       0   271.6    .035       0
Bank Sta=142,271.6
XS Rating Curve= 0 ,0
Exp/Cntr(USF)=0,0
Exp/Cntr=0.5,0.3

Type RM Length L Ch R = 1 ,6439    ,34.7,29.5,78.6
XS GIS Cut Line= 3
2041670.27859266219819.4285588712041790.44681727220179.933232701
2041824.59565662220298.031302121
#Sta/Elev= 30
       0 1682.98    48.3 1674.74    55.3 1674.02    65.6 1672.28      76 1671.02
    79.5 1670.42    93.3 1667.88   114.1 1662.74   124.4 1661.07   138.3 1658.22
   141.7  1657.4   145.2 1656.22     155 1650.61     159  1647.8   160.6 1647.21
   162.5 1646.66   165.3 1646.56   224.7 1646.56   228.2 1646.83   230.7 1647.32
     242 1649.43   248.9  1650.5   255.8 1651.32   266.9 1652.05   290.7 1653.04
   332.2 1653.42   397.4 1653.43   420.8 1653.82   455.3 1653.63   502.9 1653.76
#Mann= 4 ,-1 , 0
       0      .1       0   160.6    .045       0   230.7      .1       0
     250    .035       0
Bank Sta=160.6,230.7
XS Rating Curve= 0 ,0
Exp/Cntr(USF)=0,0
Exp/Cntr=0.5,0.3

Type RM Length L Ch R = 1 ,6410    ,53.7,56.5,94
XS GIS Cut Line= 4
2041641.23340673219826.4101146232041682.02113664219967.681523509
2041729.85016738220065.8135003852041807.93625089220301.999549629
#Sta/Elev= 30
       0 1678.56    37.1 1672.09    57.5  1669.5    65.3 1668.15    81.4 1664.62
    91.7 1661.37    95.1 1660.56   108.8 1658.53   120.9 1655.45   129.3 1654.01
   139.4 1650.58   142.9 1649.64   149.9 1646.93   154.8 1645.64   171.8 1640.06
   176.9  1639.6   186.4 1639.44   208.3 1639.68   210.8    1640   216.1 1640.84
   218.6 1641.71   222.9 1643.71   230.2 1646.17   237.5 1647.56   256.2 1649.21
   286.9 1651.09   300.7 1651.71   331.8 1652.35   438.9 1652.92     505 1653.63
#Mann= 4 ,-1 , 0
       0      .1       0   171.8    .045       0   210.8      .1       0
  247.04    .035       0
Bank Sta=171.8,210.8
XS Rating Curve= 0 ,0
Exp/Cntr(USF)=0,0
Exp/Cntr=0.5,0.3

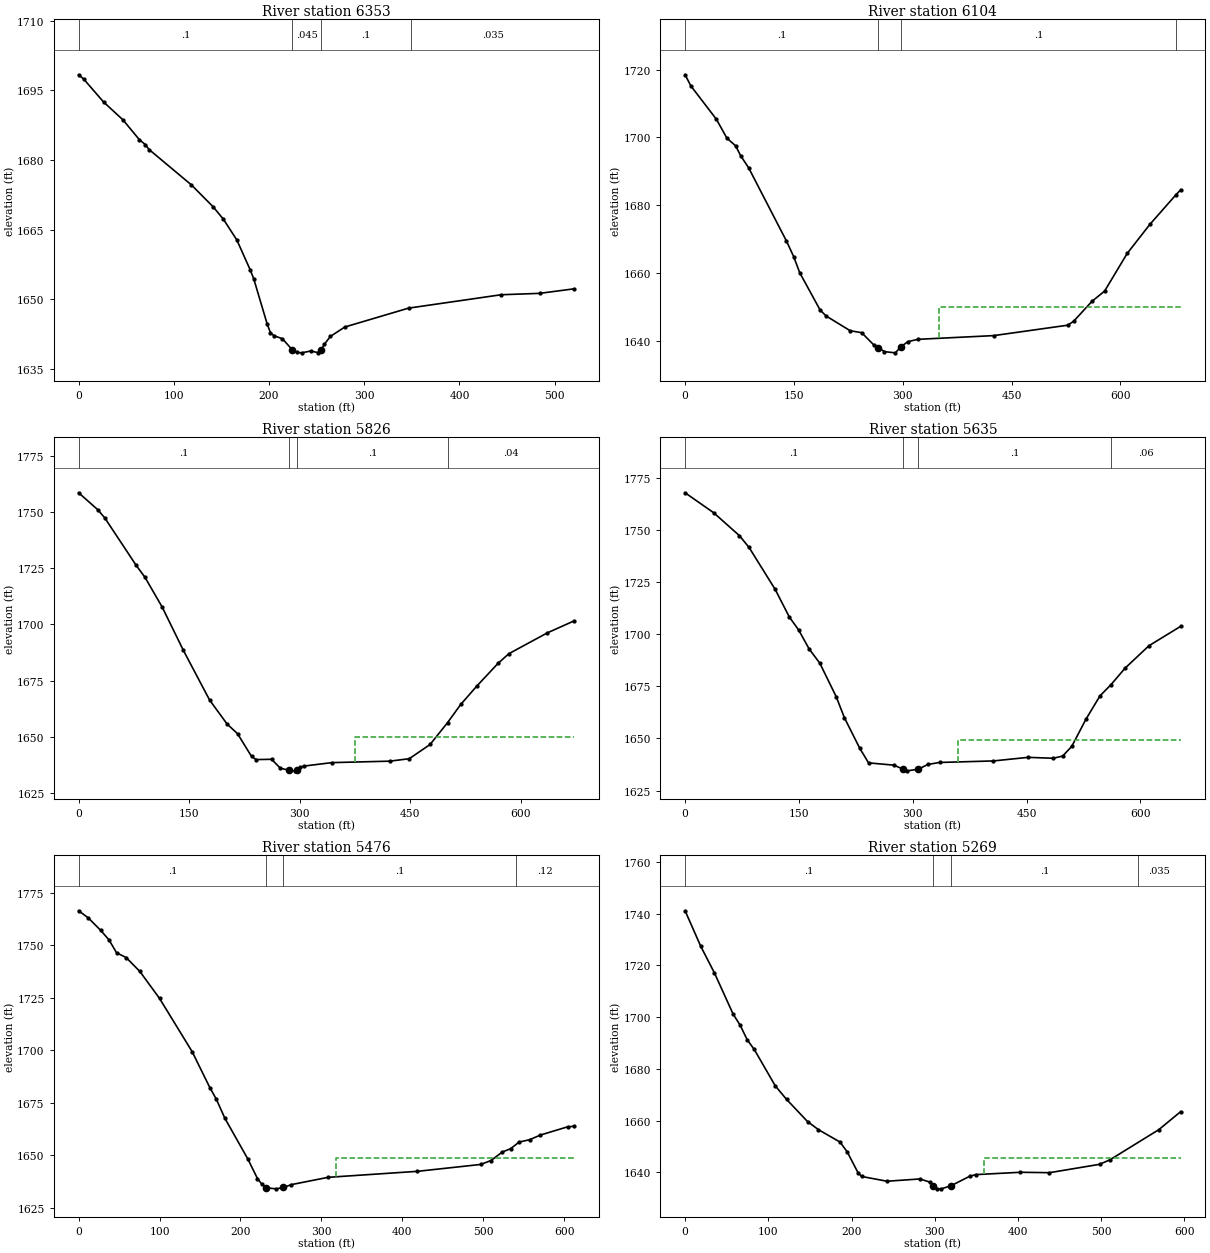
Type RM Length L Ch R = 1 ,6353    ,253.8,249.8,230.9
XS GIS Cut Line= 4
2041576.88775126219827.4986581222041597.54065445219893.391254007
2041706.33249486220163.005815043 2041765.2205517220312.490882417
#Sta/Elev= 30
       0 1698.39     5.2 1697.49    26.3  1692.5    46.5 1688.68    63.7 1684.42
      70 1683.34    74.1 1682.25   118.5 1674.63   141.4 1669.89     152 1667.26
   166.2 1662.75   180.3 1656.28   183.9  1654.4     198 1644.67   201.5 1642.75
     205 1642.14   214.1 1641.45   224.21639.128   229.2  1638.5   234.3 1638.42
   243.9 1638.82     251 1638.49   254.6 1638.98   258.1 1640.27   264.5 1641.97
   279.6 1643.99   346.5 1648.06   443.8 1650.95   484.3 1651.25   520.5 1652.23
#Mann= 4 ,-1 , 0
       0      .1       0   224.2    .045       0   254.6      .1       0
  349.05    .035       0
Bank Sta=224.2,254.6
XS Rating Curve= 0 ,0
Exp/Cntr(USF)=0,0
Exp/Cntr=0.3,0.1

Type RM Length L Ch R = 1 ,6104    ,285,277.1,262.4
XS GIS Cut Line= 4
2041342.37461685219979.840081139 2041386.5871948220056.414442952
 2041648.8630939220467.5496361372041721.39960245220546.130853735
#Sta/Elev= 30
       0 1718.45     7.9 1715.18    43.2 1705.31    57.6 1699.75    69.6  1697.5
    76.8  1694.5    87.5 1691.03   139.7 1669.41   149.7 1664.79     158 1660.05
   186.2 1649.01   194.6 1647.26   227.5 1642.95   243.4 1642.36   259.8 1638.82
   266.4 1637.95   274.8 1636.77   289.8 1636.42   297.5 1638.22     307 1639.72
   320.9 1640.41   425.3  1641.5   527.2 1644.57   535.5 1645.72   560.6 1651.58
   578.2 1654.64   609.3 1665.73   640.5 1674.29   676.2 1682.97     683  1684.5
#Mann= 4 ,-1 , 0
       0      .1       0   266.4    .045       0   297.5      .1       0
   676.2     .04       0
#XS Ineff= 2 , 0
       0                     350       0    1650
Permanent Ineff=
       F       F
Bank Sta=266.4,297.5
XS Rating Curve= 0 ,0
Exp/Cntr(USF)=0,0
Exp/Cntr=0.3,0.1

Type RM Length L Ch R = 1 ,5826    ,187.5,191.2,194.3
XS GIS Cut Line= 3
2041092.68379108220272.161801635     2041336.439      220430.424
2041658.94098334220635.272585944
#Sta/Elev= 30
       0 1758.64      26  1751.1    35.5 1747.45    78.2 1726.29    90.1 1720.99
   113.4 1707.76   142.2 1688.47   177.8 1666.36   201.5  1655.7   215.8 1651.34
   234.7 1641.26   240.9 1639.85     262 1639.98   273.8 1636.01   285.5 1635.11
   293.3 1634.84   297.11635.094   301.1 1636.45   305.9 1636.96   343.8  1638.5
   422.4 1639.15   448.8 1640.24   477.1 1646.57   500.8 1656.29   518.7  1664.4
   541.2 1672.82   569.3 1682.67     584 1686.99   636.3 1696.27   672.7 1701.62
#Mann= 4 ,-1 , 0
       0      .1       0   285.5    .045       0   297.1      .1       0
   500.8     .04       0
#XS Ineff= 2 , 0
       0                     375       0    1650
Permanent Ineff=
       F       F
Bank Sta=285.5,297.1
XS Rating Curve= 0 ,0
Exp/Cntr(USF)=0,0
Exp/Cntr=0.3,0.1

Type RM Length L Ch R = 1 ,5635    ,160.1,158.8,157
XS GIS Cut Line= 4
2041014.28878538220383.6020457122041114.60238835220465.730141713
2041291.82410886220642.9518622222041507.73298112220809.477322216
#Sta/Elev= 30
       0 1767.73    37.7 1758.15    71.6 1747.18    84.3 1741.52   118.7 1721.42
   137.3 1708.22   149.6 1701.99   163.5 1692.86   177.5 1686.07   199.2 1669.93
   209.9 1659.93   230.1 1645.32   241.7 1638.31   274.9 1637.22   287.7 1635.25
   292.7 1634.49   307.4 1635.29   319.8 1637.55   335.2  1638.5   406.3 1639.24
   451.9 1640.95   485.1 1640.52   497.5 1641.58   509.5 1646.25   528.2 1659.26
   546.6  1670.4     561 1675.73   579.7 1683.69   611.1 1694.42   652.9 1703.73
#Mann= 4 ,-1 , 0
       0      .1       0   287.7    .045       0   307.4      .1       0
     561     .06       0
#XS Ineff= 2 , 0
       0                     360       0 1649.29
Permanent Ineff=
       F       F
Bank Sta=287.7,307.4
XS Rating Curve= 0 ,0
Exp/Cntr(USF)=0,0
Exp/Cntr=0.3,0.1

Type RM Length L Ch R = 1 ,5476    ,201.6,207.1,208.7
XS GIS Cut Line= 3
2040912.97299623220530.660802501      2041108.59      220670.838
2041389.95135308220913.793887638
#Sta/Elev= 30
       0 1766.41    11.7  1763.1    27.3 1757.09    37.5 1752.57    46.9 1746.41
    58.7 1744.18    75.7 1737.53     100  1724.7   140.3 1699.37   162.1 1682.33
   170.1 1676.81   180.7 1667.72   209.2 1648.25     221 1639.01   226.4 1636.34
     232 1634.59   244.4 1634.12   253.1 1634.76     263 1636.13   308.3  1639.6
   418.7 1642.45     497 1645.73   509.6  1647.6   523.5 1651.61   534.2 1653.29
   544.2 1656.35   557.7 1657.54   570.7 1659.72   604.4 1663.64   612.4 1663.89
#Mann= 4 ,-1 , 0
       0      .1       0     232    .045       0   253.1      .1       0
  540.66     .12       0
#XS Ineff= 2 , 0
                          318.63         1648.91
Permanent Ineff=
       F       F
Bank Sta=232,253.1
XS Rating Curve= 0 ,0
Exp/Cntr(USF)=0,0
Exp/Cntr=0.3,0.1

Type RM Length L Ch R = 1 ,5269    ,139.4,142.5,145.3
XS GIS Cut Line= 4
 2040818.8128059220620.9965762812040891.30302051220710.296116015
2041112.83017114220967.267610753 2041195.9844399221081.415743329
#Sta/Elev= 30
       0  1741.1    18.9 1727.32    35.3 1717.05    57.7 1701.19    66.2 1696.86
    74.6 1691.27    83.1 1687.52   108.4 1673.43   121.9 1668.24   147.1 1659.67
   160.3 1656.51   186.2 1651.73   194.9  1647.9   207.9 1639.83   212.2 1638.44
   242.6  1636.6   282.1 1637.48   294.5 1636.23   298.4 1634.87     303  1633.7
   307.8 1633.66   319.3 1634.81   342.2 1638.55   349.5 1639.16     403 1640.06
   437.9  1639.9     498 1643.13   510.6 1644.89   569.3 1656.53   595.5 1663.48
#Mann= 4 ,-1 , 0
       0      .1       0   298.4    .045       0   319.3      .1       0
   544.3    .035       0
#XS Ineff= 2 , 0
                          358.92         1645.39
Permanent Ineff=
       F       F
Bank Sta=298.4,319.3
XS Rating Curve= 0 ,0
Exp/Cntr(USF)=0,0
Exp/Cntr=0.3,0.1

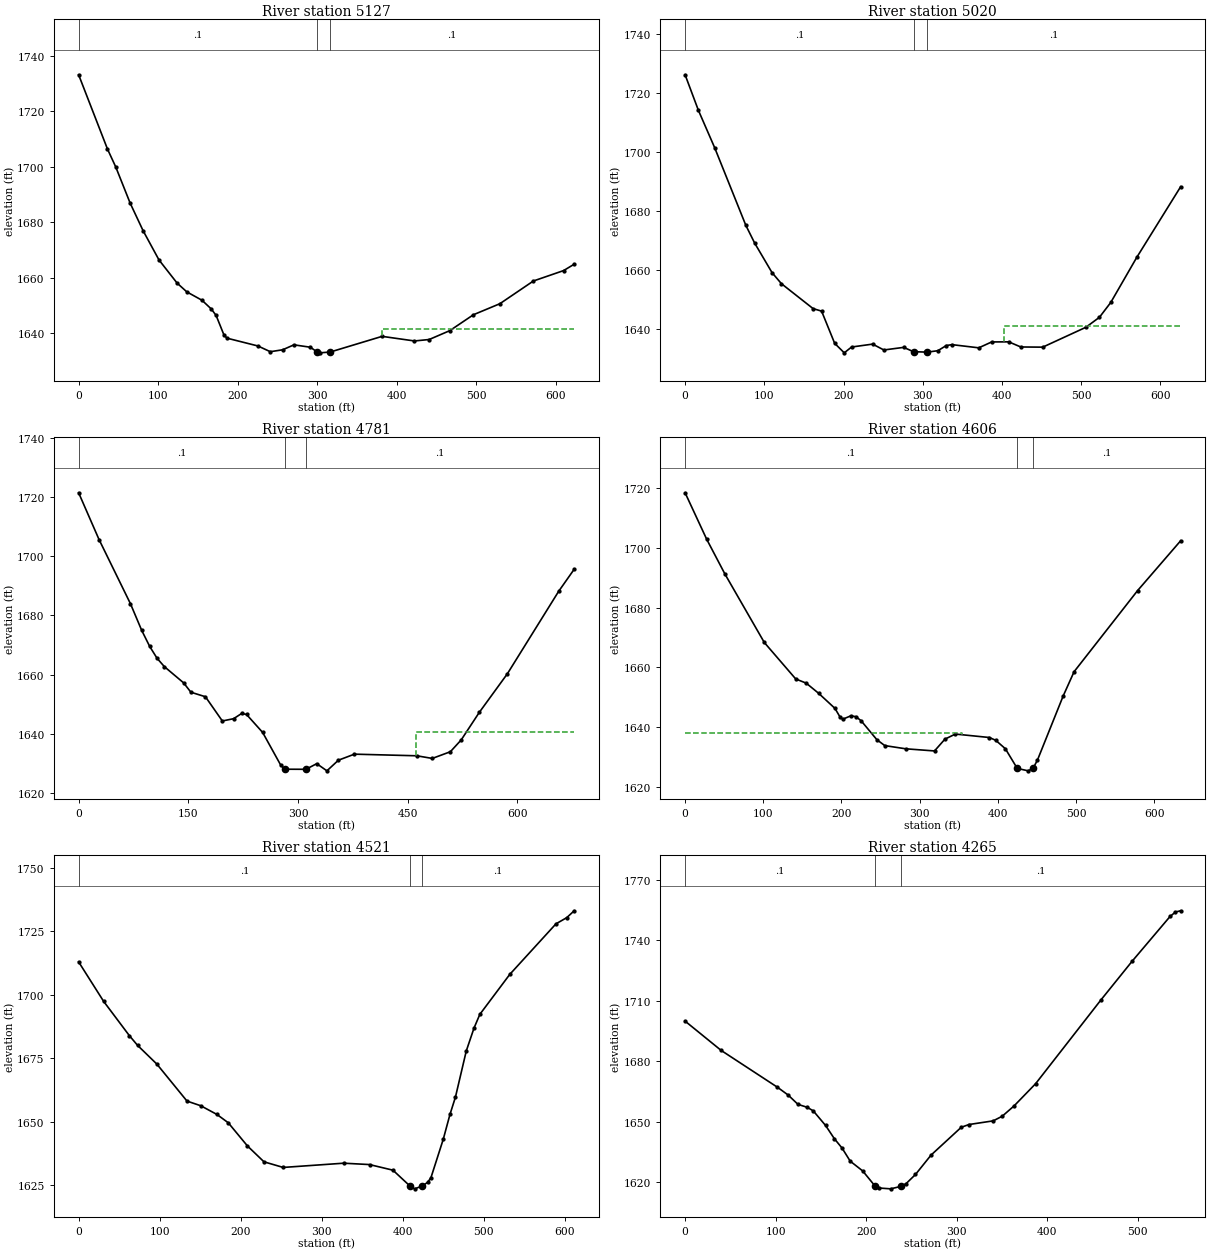
Type RM Length L Ch R = 1 ,5127    ,103.9,107.2,108.8
XS GIS Cut Line= 3
2040740.76237487220682.145995786     2040910.397      220949.186
2041052.87818736 221221.04327797
#Sta/Elev= 30
       0  1733.2    36.3 1706.37    46.7 1699.91    64.8 1686.86    81.1 1676.89
   101.1 1666.33   123.9 1657.97   136.1 1654.81   155.2 1651.78   166.8 1648.65
   172.9 1646.32   182.8 1639.25   186.7 1638.09   225.5 1635.28   241.1 1633.21
   256.6  1633.9   270.8 1635.69   291.6 1634.82     3001633.098   303.3  1632.8
   316.4 1633.09   381.7 1638.75   422.4 1637.09   440.9 1637.61   466.9 1640.82
   496.6 1646.56   529.8 1650.53     572 1658.74     610  1662.5   623.3  1664.8
#Mann= 3 ,-1 , 0
       0      .1       0     300    .045       0   316.4      .1       0
#XS Ineff= 2 , 0
                          382.01         1641.36
Permanent Ineff=
       F       F
Bank Sta=300,316.4
XS Rating Curve= 0 ,0
Exp/Cntr(USF)=0,0
Exp/Cntr=0.3,0.1

Type RM Length L Ch R = 1 ,5020    ,243.2,238.6,225.6
XS GIS Cut Line= 4
2040682.74996699220726.520374232 2040747.7534269220844.984623602
  2040921.430713221243.7334947462040955.38744978221287.499955483
#Sta/Elev= 30
       0 1726.09    16.8 1714.02    37.3 1701.36    76.7 1674.99    87.9 1668.94
   109.8 1658.94   121.6 1655.21   161.6 1646.75   172.3  1645.9   188.8 1634.97
   200.9 1631.75   210.1 1633.72   236.7 1634.71   250.9 1632.72   275.8  1633.6
   288.4 1632.14   305.61631.992     319 1632.47   329.8 1634.24   336.9 1634.53
   370.7 1633.45     387 1635.45   408.5 1635.48   423.7 1633.74   451.4 1633.68
   505.9 1640.42     523 1643.81   537.3 1648.84   570.1 1664.13   625.5  1688.1
#Mann= 3 ,-1 , 0
       0      .1       0   288.4    .045       0   305.6      .1       0
#XS Ineff= 2 , 0
                             403         1640.75
Permanent Ineff=
       F       F
Bank Sta=288.4,305.6
XS Rating Curve= 0 ,0
Exp/Cntr(USF)=0,0
Exp/Cntr=0.3,0.1

Type RM Length L Ch R = 1 ,4781    ,168,174.9,172.2
XS GIS Cut Line= 3
2040542.84937142220785.754297261     2040571.652      221019.002
2040902.41647186221313.079653437
#Sta/Elev= 30
       0 1721.39    27.9 1705.61    70.9 1683.92    86.2 1674.97    97.2 1669.51
   107.2 1665.54   117.2 1662.71   143.6 1657.22   153.5 1654.07   173.4 1652.54
   196.5 1644.36   211.9 1645.13   222.9 1646.89   229.6 1646.56   251.6  1640.5
   276.2 1629.52   281.8 1628.08   310.8 1628.05   325.6 1629.95   339.5 1627.53
   355.2 1631.12   377.1 1633.16   462.4 1632.61   483.6 1631.72   508.3 1633.98
   523.1 1637.96   547.8 1647.24   586.3 1660.31   656.4 1688.13   677.6 1695.57
#Mann= 3 ,-1 , 0
       0      .1       0   281.8    .045       0   310.8      .1       0
#XS Ineff= 2 , 0
                          460.72         1640.75
Permanent Ineff=
       F       F
Bank Sta=281.8,310.8
XS Rating Curve= 0 ,0
Exp/Cntr(USF)=0,0
Exp/Cntr=0.3,0.1

Type RM Length L Ch R = 1 ,4606    ,68.7,84.8,98.5
XS GIS Cut Line= 4
2040507.96141019  220796.27103392040582.93722682221160.439286107
2040666.23143546221272.0889700272040727.87447371221378.186122406
#Sta/Elev= 30
       0 1718.43    27.6 1702.88      51  1691.2   101.3 1668.31   141.5  1656.1
   154.9  1654.7   170.7 1651.32   191.7 1646.24   198.4 1643.25   201.8 1642.64
   211.8 1643.74   218.5 1643.48   225.2 1642.09   245.3 1635.76   255.4 1633.79
   282.2 1632.72     319    1632   332.4 1635.97   345.7 1637.65   389.2  1636.5
   397.3 1635.56   409.6 1632.75   424.8 1626.16   438.8 1625.34   445.1 1626.21
   450.6  1628.9   483.5 1650.36   497.5 1658.52   578.7 1685.67   633.8 1702.36
#Mann= 3 ,-1 , 0
       0      .1       0   424.8    .045       0   445.1      .1       0
#XS Ineff= 2 , 0
          353.67 1637.97
Permanent Ineff=
       F       F
Bank Sta=424.8,445.1
XS Rating Curve= 0 ,0
Exp/Cntr(USF)=0,0
Exp/Cntr=0.3,0.1

Type RM Length L Ch R = 1 ,4521    ,251.2,256.6,250.8
XS GIS Cut Line= 3
 2040459.3667568220805.426158054     2040551.083      221157.005
2040500.18515924221399.748825786
#Sta/Elev= 30
       0 1712.87    30.8 1697.36    62.5 1683.89    72.7 1680.03    96.5 1672.66
   133.7  1658.1   150.7 1656.26   170.7 1652.83   184.6 1649.57   208.3 1640.44
   228.7  1634.2   252.4 1631.99     327 1633.66   358.9 1633.12   387.8 1630.91
   409.11624.589   414.6 1623.57   423.61624.656   430.5 1626.09   434.7 1627.97
   449.9  1643.1   458.2  1652.9   464.9 1659.65   478.3 1677.85   487.8  1686.8
     495 1692.22   531.9 1707.93   588.9 1727.83   602.3 1730.29   611.4 1732.98
#Mann= 3 ,-1 , 0
       0      .1       0   409.1    .045       0   423.6      .1       0
Bank Sta=409.1,423.6
XS Rating Curve= 0 ,0
Exp/Cntr(USF)=0,0
Exp/Cntr=0.3,0.1

Type RM Length L Ch R = 1 ,4265    ,164.6,152.9,137.3
XS GIS Cut Line= 4
2040392.01981118220820.772811488 2040435.8431988220988.534217214
2040386.22111706221149.8059828762040363.55000133221353.846024434
#Sta/Elev= 30
       0 1699.94    39.9  1685.4     102 1667.17   113.8 1663.32   124.7 1658.68
   134.9 1657.23   141.6 1655.45   155.2 1648.21   164.9 1641.65   173.4 1637.01
   182.4 1630.53   196.2 1625.68   209.9 1618.15   213.9 1617.23   227.1 1616.81
   238.31618.014   244.2 1619.42   254.5 1623.93   271.7 1633.54   305.1 1647.34
   313.7  1648.7   340.3  1650.5   350.3  1652.8   363.4 1657.91   387.2 1668.93
   459.2 1710.36   493.6 1729.51   535.7 1751.81   541.7 1754.03   547.4 1754.64
#Mann= 3 ,-1 , 0
       0      .1       0   209.9    .045       0   238.3      .1       0
Bank Sta=209.9,238.3
XS Rating Curve= 0 ,0
Exp/Cntr(USF)=0,0
Exp/Cntr=0.3,0.1