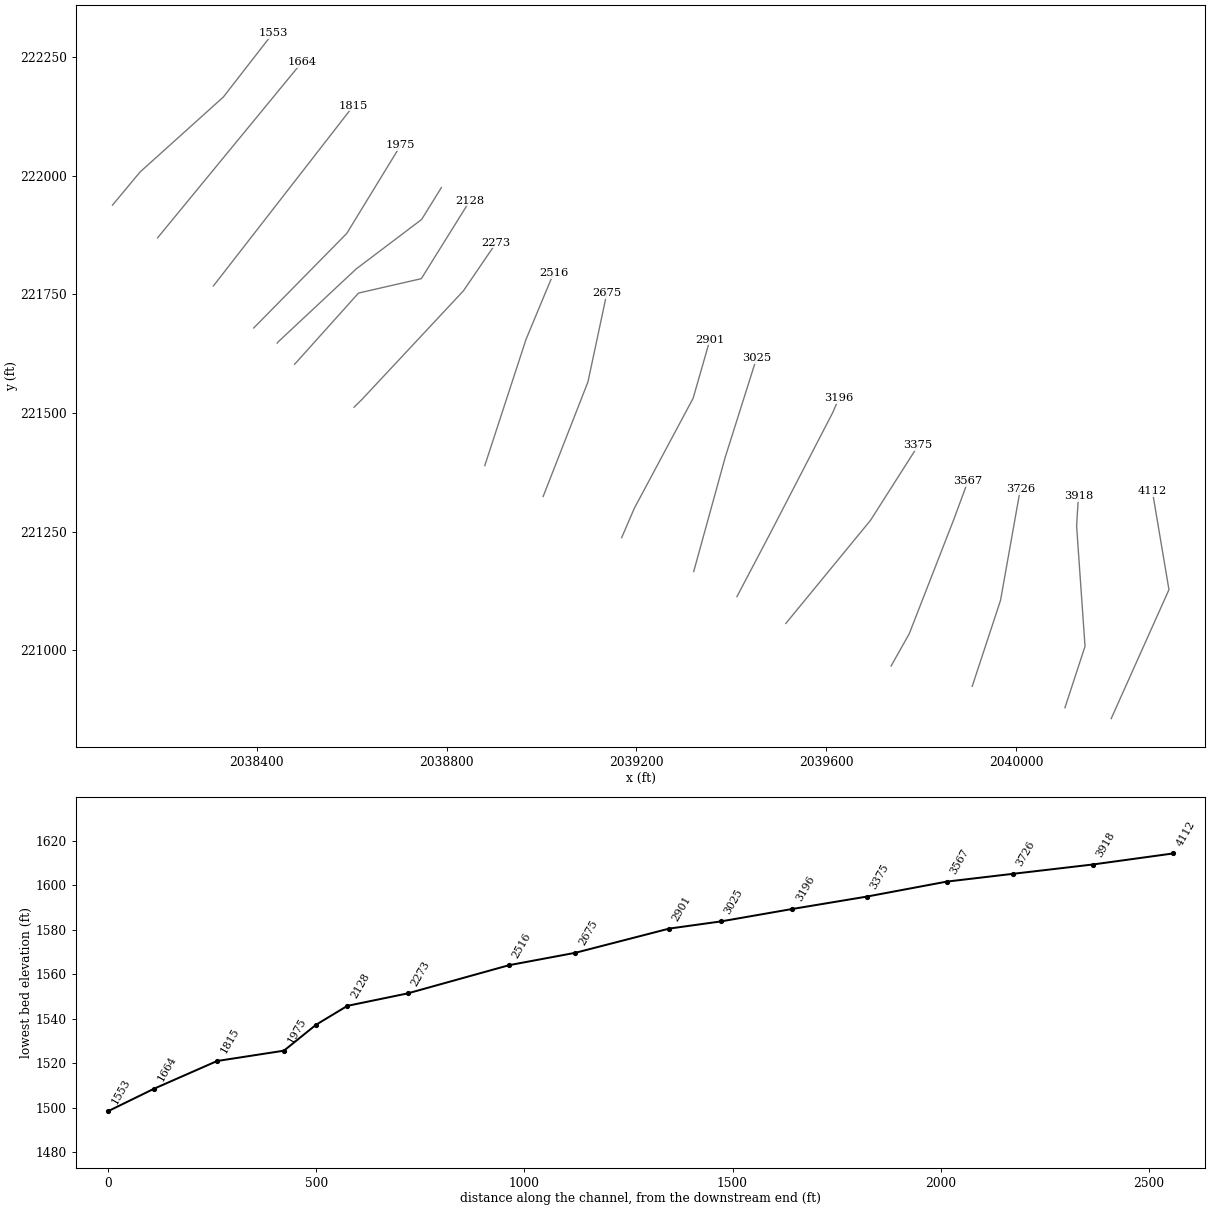
HEC-RAS study STONYCK.prj: STONYCK

--- STONYCK.g01 (geometry) --- (continued)

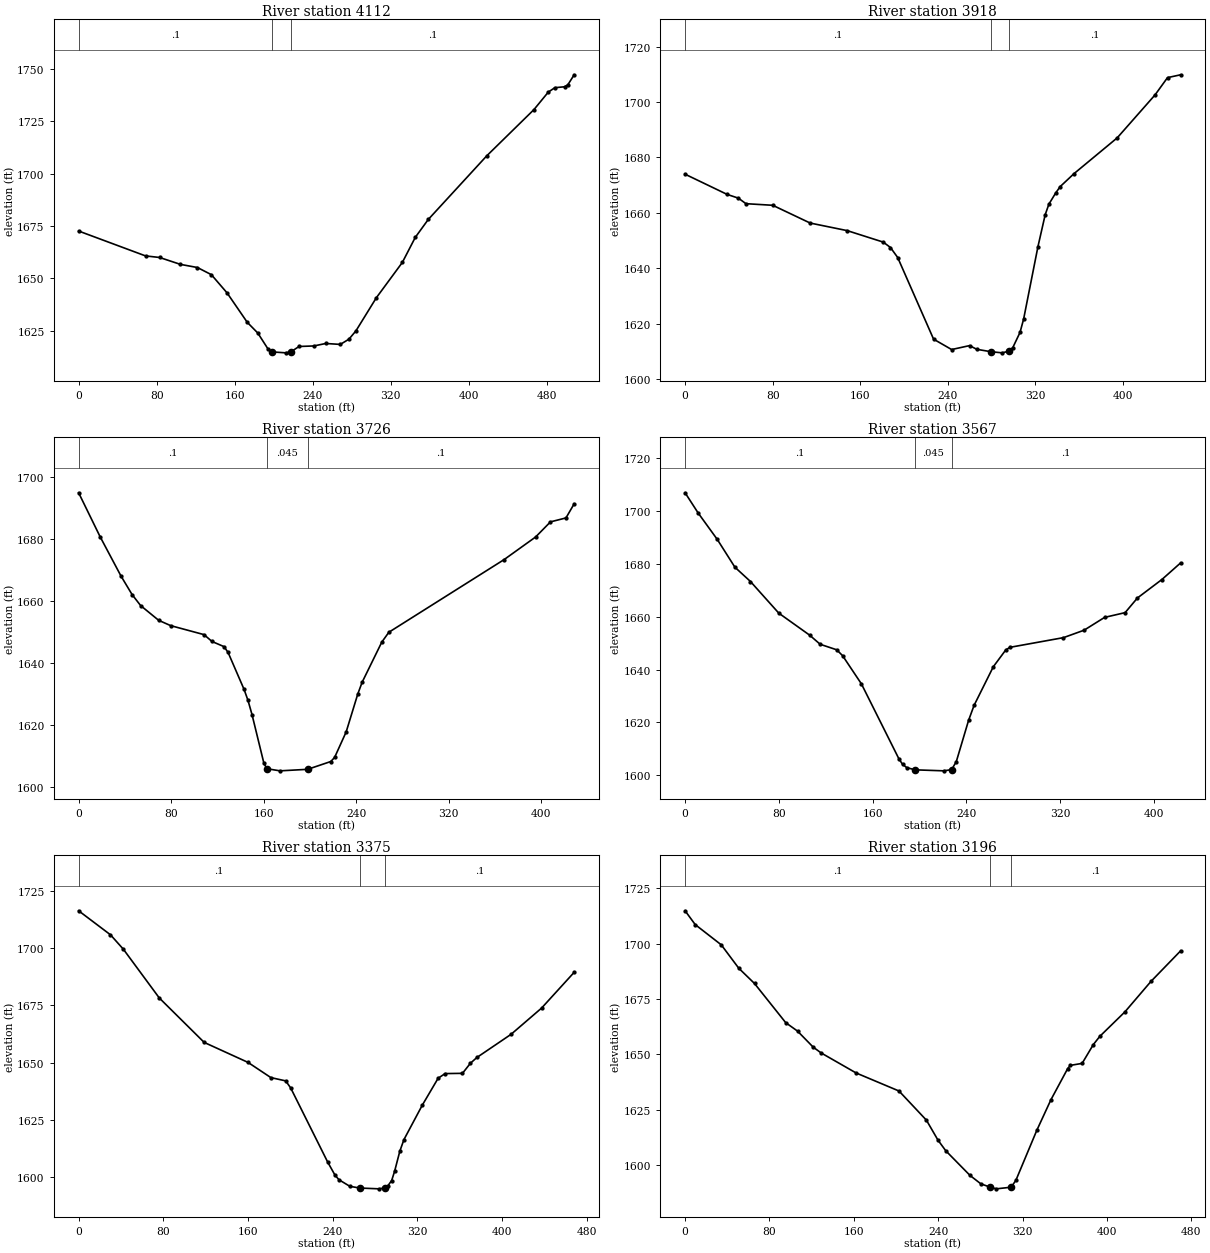
Type RM Length L Ch R = 1 ,4112    ,181.4,193.9,202
XS GIS Cut Line= 3
2040200.39779971220855.815746694     2040322.086      221127.509
2040287.12527798221334.957295037
#Sta/Elev= 30
       0 1672.64    68.6 1660.75      83    1660   104.4  1656.7   121.8  1655.2
   136.1 1651.78   152.2 1643.07   172.9 1629.01   183.7 1623.89   194.4 1616.11
   198.51614.863   212.4 1614.42   217.91614.991     226 1617.46   241.2 1617.71
   253.4 1618.89   268.3 1618.45   277.1 1620.93   284.3  1624.9   305.3 1640.78
   331.9 1657.62   345.2 1669.62   358.5 1678.17   418.4 1708.55   466.9  1730.7
   481.6 1739.06   488.3 1741.15   498.2 1741.58   501.6 1742.53   508.1 1747.32
#Mann= 3 ,-1 , 0
       0      .1       0   198.5    .045       0   217.9      .1       0
Bank Sta=198.5,217.9
XS Rating Curve= 0 ,0
Exp/Cntr(USF)=0,0
Exp/Cntr=0.3,0.1

Type RM Length L Ch R = 1 ,3918    ,203.4,192,187.9
XS GIS Cut Line= 4
2040102.88733034220878.7080774232040145.19957717 221008.02860647
2040127.47740512221261.4556667972040131.23425045 221324.16608506
#Sta/Elev= 30
       0 1673.91    38.4 1666.62    48.7 1665.27    55.6 1663.27    80.1 1662.69
   114.3 1656.28   148.2 1653.54   181.1  1649.4   187.7 1647.45   194.3 1643.84
   227.1 1614.37   243.6 1610.62     260 1612.04   266.6  1610.7   279.2 1609.86
   289.6 1609.43   295.6 1609.98   299.5 1611.32   306.1  1616.8   309.4 1621.63
   322.5 1647.79   329.1 1659.28   332.5 1663.11   338.7 1667.13   342.8 1669.43
   355.4  1674.1   394.9 1687.02   429.5 1702.53   440.9 1708.77   452.9  1709.8
#Mann= 3 ,-1 , 0
       0      .1       0   279.2    .045       0   295.6      .1       0
Bank Sta=279.2,295.6
XS Rating Curve= 0 ,0
Exp/Cntr(USF)=0,0
Exp/Cntr=0.3,0.1

Type RM Length L Ch R = 1 ,3726    ,157.8,158.9,156.2
XS GIS Cut Line= 3
2039907.41776652220923.724414955     2039967.152      221105.033
2040008.79094306221338.859894949
#Sta/Elev= 30
       0 1694.99    18.6 1680.78    36.7 1668.06    46.2 1662.14    53.6 1658.58
    69.2 1653.82    79.6  1652.1   108.4  1649.2   115.3 1646.99   125.7 1645.32
   129.2 1643.45     143 1631.54   146.4 1627.99   149.9 1623.38   160.2 1607.63
   162.8 1605.91   174.1 1605.23     198 1605.72     218 1608.24   221.3 1609.56
   231.3 1617.81   241.3    1630   245.1 1633.84   262.1 1646.79   268.2 1649.97
   367.9 1673.44   395.1 1680.73   407.9  1685.6   421.3 1686.87   428.4 1691.43
#Mann= 3 ,-1 , 0
       0      .1       0   162.8    .045       0     198      .1       0
Bank Sta=162.8,198
XS Rating Curve= 0 ,0
Exp/Cntr(USF)=0,0
Exp/Cntr=0.3,0.1

Type RM Length L Ch R = 1 ,3567    ,198.2,191.7,187.9
XS GIS Cut Line= 4
2039736.54332096220966.675765567 2039774.8061813221034.611864546
2039868.73369317221275.6334044372039898.65185439221356.647751118
#Sta/Elev= 30
       0 1706.75    11.2 1699.08    27.5 1689.11    42.5 1678.65    55.8 1673.24
      80 1661.28   106.3 1652.98   115.3 1649.53   129.4 1647.45   134.4 1645.25
   150.5 1634.58   182.5 1606.27   185.7 1604.15   189.2 1602.96   196.2 1602.11
   220.9 1601.73   227.5 1602.19   231.5 1605.21     242 1620.82   246.7 1626.48
   263.1 1641.05   273.7 1647.38   277.2 1648.37     323 1652.04   340.6 1654.85
   358.1 1659.69   375.6 1661.48   386.1 1667.01     407 1673.99     423 1680.27
#Mann= 3 ,-1 , 0
       0      .1       0   196.2    .045       0   227.5      .1       0
Bank Sta=196.2,227.5
XS Rating Curve= 0 ,0
Exp/Cntr(USF)=0,0
Exp/Cntr=0.3,0.1

Type RM Length L Ch R = 1 ,3375    ,174.5,179.1,180.2
XS GIS Cut Line= 3
2039514.75021896221056.359145506     2039693.178      221273.692
2039793.59229377221431.315623321
#Sta/Elev= 30
       0 1716.21    30.1 1705.73    42.3 1699.43    76.2  1678.2   118.6 1658.83
     160 1650.12   181.6 1643.49   195.6 1642.06   200.3 1638.99   235.2 1606.72
   242.2 1600.94     246 1598.94   256.2  1596.1   265.5 1595.35     284    1595
     289 1595.41   291.8 1596.13   295.7 1598.62   298.5 1602.69   303.4  1611.4
   307.3 1616.47   324.6 1631.45   339.6 1643.22   346.2 1645.24   362.6 1645.35
   370.1 1649.75   376.2 1652.26   408.5 1662.36   437.3 1673.79   468.1 1689.39
#Mann= 3 ,-1 , 0
       0      .1       0   265.5    .045       0     289      .1       0
Bank Sta=265.5,289
XS Rating Curve= 0 ,0
Exp/Cntr(USF)=0,0
Exp/Cntr=0.3,0.1

Type RM Length L Ch R = 1 ,3196    ,166.5,170.9,173.4
XS GIS Cut Line= 4
 2039411.6718298221112.8490447212039482.39034247221247.277929156
2039613.53441564221500.7049894832039626.52362004221530.525275631
#Sta/Elev= 30
       0 1714.75     9.6 1708.52    34.3  1699.4    50.9 1688.85    65.8 1681.98
    95.4 1664.32   106.6 1660.52   121.4 1653.31     129 1650.67   162.1 1641.66
   202.8 1633.52   228.8 1620.37   239.7 1611.42   247.1 1606.61   270.1 1595.48
   280.3 1591.71     2891590.215   295.1 1589.43   309.1 1590.17   313.6 1593.26
   333.4 1615.76   346.8 1629.56   362.7 1643.61   365.3 1645.08   376.4 1645.97
     387 1654.43   393.2 1658.17     417  1669.2   441.6 1682.88   469.8  1696.7
#Mann= 3 ,-1 , 0
       0      .1       0     289    .045       0   309.1      .1       0
Bank Sta=289,309.1
XS Rating Curve= 0 ,0
Exp/Cntr(USF)=0,0
Exp/Cntr=0.3,0.1

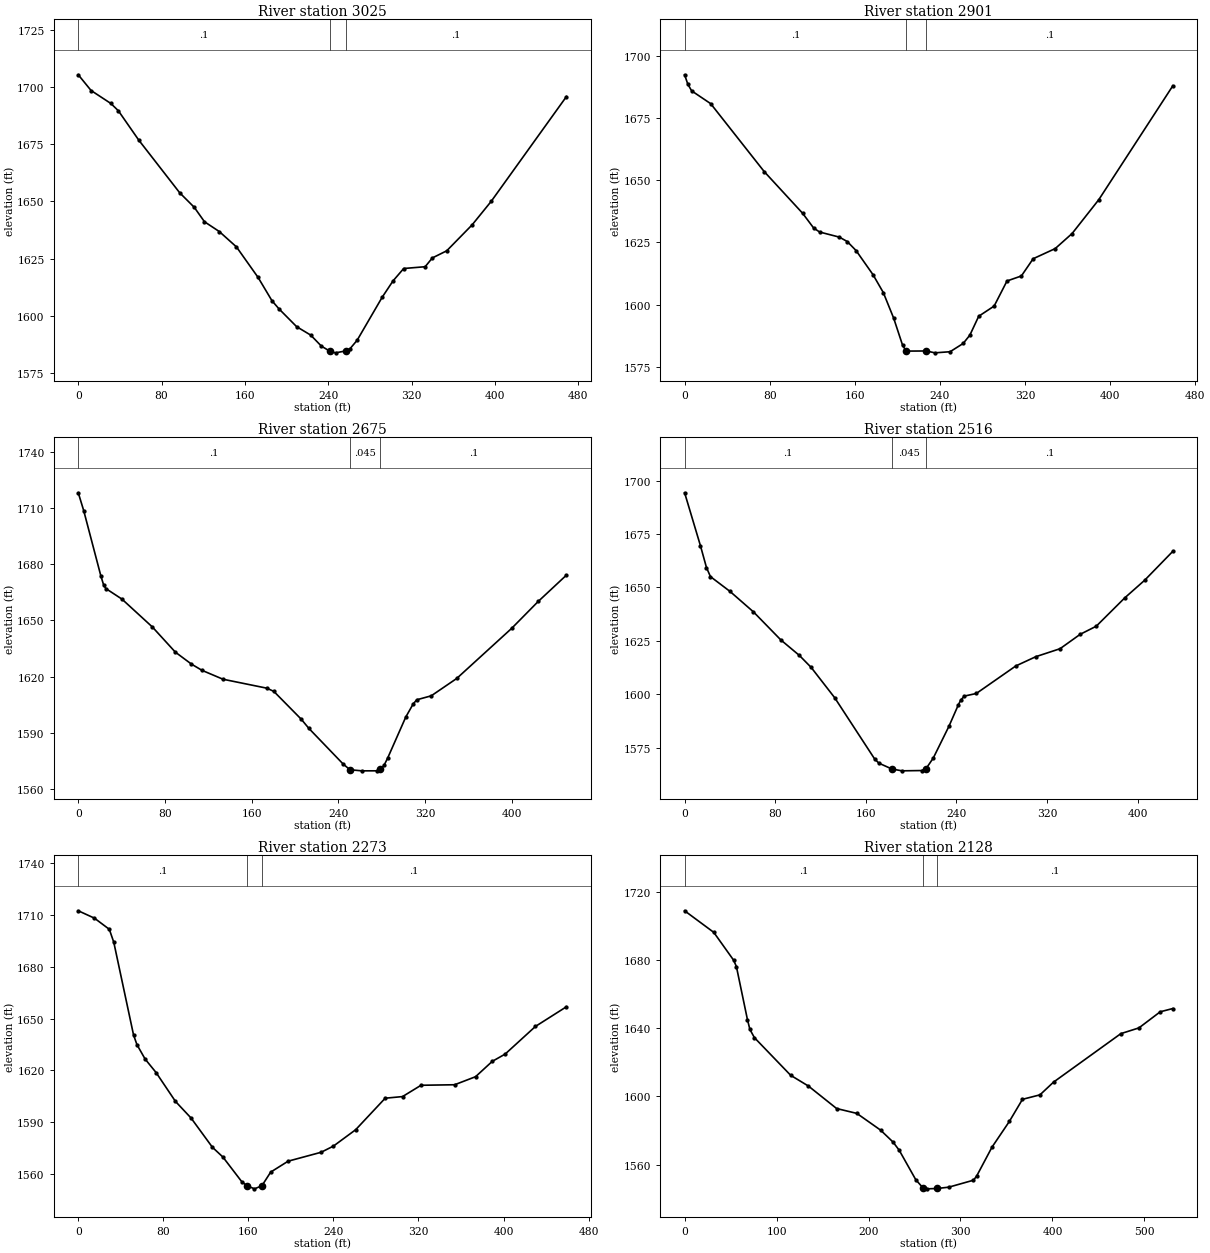
Type RM Length L Ch R = 1 ,3025    ,128.3,124.6,121.4
XS GIS Cut Line= 3
2039320.59214367221165.750172846     2039386.909      221406.253
2039453.02282682221615.346317986
#Sta/Elev= 30
       0 1705.35    12.3 1698.48    31.3 1692.81    38.5 1689.63      58 1676.86
    97.4 1653.79   111.4 1647.43   121.2 1641.13   135.4 1636.86   151.9 1630.14
   172.7 1616.78     186 1606.62   192.7 1603.08   209.7 1595.28   223.2  1591.6
   233.5 1586.76     242 1584.47   247.1 1583.85     2571584.703   260.9 1585.62
   267.8 1589.36   291.9  1608.2   302.3 1615.31   312.5  1620.7   333.1 1621.48
     340 1625.32   353.8 1628.43   378.2 1639.77   396.5 1650.03   468.8 1695.85
#Mann= 3 ,-1 , 0
       0      .1       0     242    .045       0     257      .1       0
Bank Sta=242,257
XS Rating Curve= 0 ,0
Exp/Cntr(USF)=0,0
Exp/Cntr=0.3,0.1

Type RM Length L Ch R = 1 ,2901    ,222.9,225.4,233.4
XS GIS Cut Line= 4
2039168.78068759221237.1826711812039195.29115524221298.672228104
 2039319.3463596 221530.832681972039354.88029272 221654.67889006
#Sta/Elev= 30
       0 1692.38       3  1688.6     6.6 1685.92    24.5 1680.77    74.8 1653.48
   110.9 1636.73   121.3 1630.79   126.9 1629.18   145.5 1627.12   152.9 1625.35
   161.2 1621.72   177.1 1612.04   186.8 1604.84   196.5  1594.6     205 1583.57
   208.4 1581.31   227.3 1581.36   235.3 1580.61   249.6 1581.06   261.9 1584.38
   268.2 1587.74   276.5 1595.32     291 1599.41   303.1  1609.5   316.6 1611.51
   327.7 1618.44   348.4 1622.51   364.3 1628.57   389.4 1642.18     459 1687.95
#Mann= 3 ,-1 , 0
       0      .1       0   208.4    .045       0   227.3      .1       0
Bank Sta=208.4,227.3
XS Rating Curve= 0 ,0
Exp/Cntr(USF)=0,0
Exp/Cntr=0.3,0.1

Type RM Length L Ch R = 1 ,2675    ,157.8,159,156.7
XS GIS Cut Line= 3
2039003.30487824221323.859343946      2039097.73       221565.39
2039137.58788373221752.476247971
#Sta/Elev= 30
       0 1718.14       5 1708.66    20.9 1673.67    23.4 1668.97    25.5    1667
    40.3  1661.4    68.4 1646.51    89.6 1633.09   104.5 1626.68   114.2 1623.37
   133.6 1618.62   174.1 1613.84   180.5 1612.13   205.8 1597.29   212.9 1592.35
   244.6 1573.29   250.8 1570.31   261.7 1569.73   275.5 1569.74   278.8 1570.47
   282.2 1572.65   285.5 1576.46   302.3 1598.46     309 1605.32   312.4 1607.65
   325.8 1609.77   349.3 1619.03     400 1645.77   424.5 1660.13   450.6 1674.21
#Mann= 3 ,-1 , 0
       0      .1       0   250.8    .045       0   278.8      .1       0
Bank Sta=250.8,278.8
XS Rating Curve= 0 ,0
Exp/Cntr(USF)=0,0
Exp/Cntr=0.3,0.1

Type RM Length L Ch R = 1 ,2516    ,251.5,243.8,237.7
XS GIS Cut Line= 3
2038880.30424782221388.9067065952038967.29291125221655.144737081
 2039025.2881307221794.520345116
#Sta/Elev= 30
       0 1694.29      14 1669.46    19.3 1659.28    22.8 1655.06      40 1648.16
    60.8 1638.54    84.9 1625.45   101.3 1618.18   111.7 1612.58   132.5 1598.37
   167.7 1569.77   171.5 1567.76     183 1565.03   191.9 1564.17   209.2 1564.31
   213.1 1565.17   219.5 1570.14   233.3 1584.96   241.7 1595.11   243.7 1597.19
   246.9 1599.14   257.5 1600.37   292.4 1613.26   310.1  1617.6   331.4 1621.31
   349.2 1628.05   363.4 1631.85   388.6 1645.13   406.1 1653.34     431  1666.9
#Mann= 3 ,-1 , 0
       0      .1       0     183    .045       0   213.1      .1       0
Bank Sta=183,213.1
XS Rating Curve= 0 ,0
Exp/Cntr(USF)=0,0
Exp/Cntr=0.3,0.1

Type RM Length L Ch R = 1 ,2273    ,155.7,144.8,135
XS GIS Cut Line= 4
2038604.78208498 221511.964165792038622.14739044221529.091590351
2038835.23723372221757.1877606252038904.38380465221858.495527337
#Sta/Elev= 30
       0 1712.42    15.2 1708.15    29.2  1701.7    33.4 1694.22      52 1640.53
    55.2 1634.92    62.9 1626.57    73.2 1618.78    91.4  1602.1   106.1 1592.45
   126.2 1575.51   136.1 1569.84     154 1555.43   158.61553.345   165.7 1551.47
   172.7 1553.23     181 1561.16   197.4 1567.48   228.4 1572.63     240 1576.21
   260.9 1585.68   288.7 1603.93     305 1604.87   322.4 1611.42     354 1611.72
   373.7 1616.38   389.4 1625.26   401.5 1629.46     430 1645.47   459.2 1656.88
#Mann= 3 ,-1 , 0
       0      .1       0   158.6    .045       0   172.7      .1       0
Bank Sta=158.6,172.7
XS Rating Curve= 0 ,0
Exp/Cntr(USF)=0,0
Exp/Cntr=0.3,0.1

Type RM Length L Ch R = 1 ,2128    ,67.3,75.2,82.3
XS GIS Cut Line= 4
2038479.59481246221602.486067343     2038614.187      221752.509
     2038746.565      221782.8912038848.90320507221947.127205634
#Sta/Elev= 30
       0 1708.75    31.7 1696.11    53.3 1679.79    56.3 1676.09    68.3 1645.04
      71 1639.23    75.9 1634.43   115.3 1612.39   134.7 1606.05   165.3 1592.91
   187.3 1590.06   213.1 1580.26   226.6  1573.3   233.3 1568.53   251.4 1551.19
   259.6 1546.21   263.6 1545.87   274.61546.075   287.2 1546.84   314.1 1550.93
   317.5 1553.28   334.3 1570.33   353.1 1585.33   367.4 1598.31   386.4 1600.92
   401.2 1608.39   474.4 1636.79     494 1640.13   517.2 1649.58   530.9 1651.49
#Mann= 3 ,-1 , 0
       0      .1       0   259.6    .045       0   274.6      .1       0
Bank Sta=259.6,274.6
XS Rating Curve= 0 ,0
Exp/Cntr(USF)=0,0
Exp/Cntr=0.3,0.1

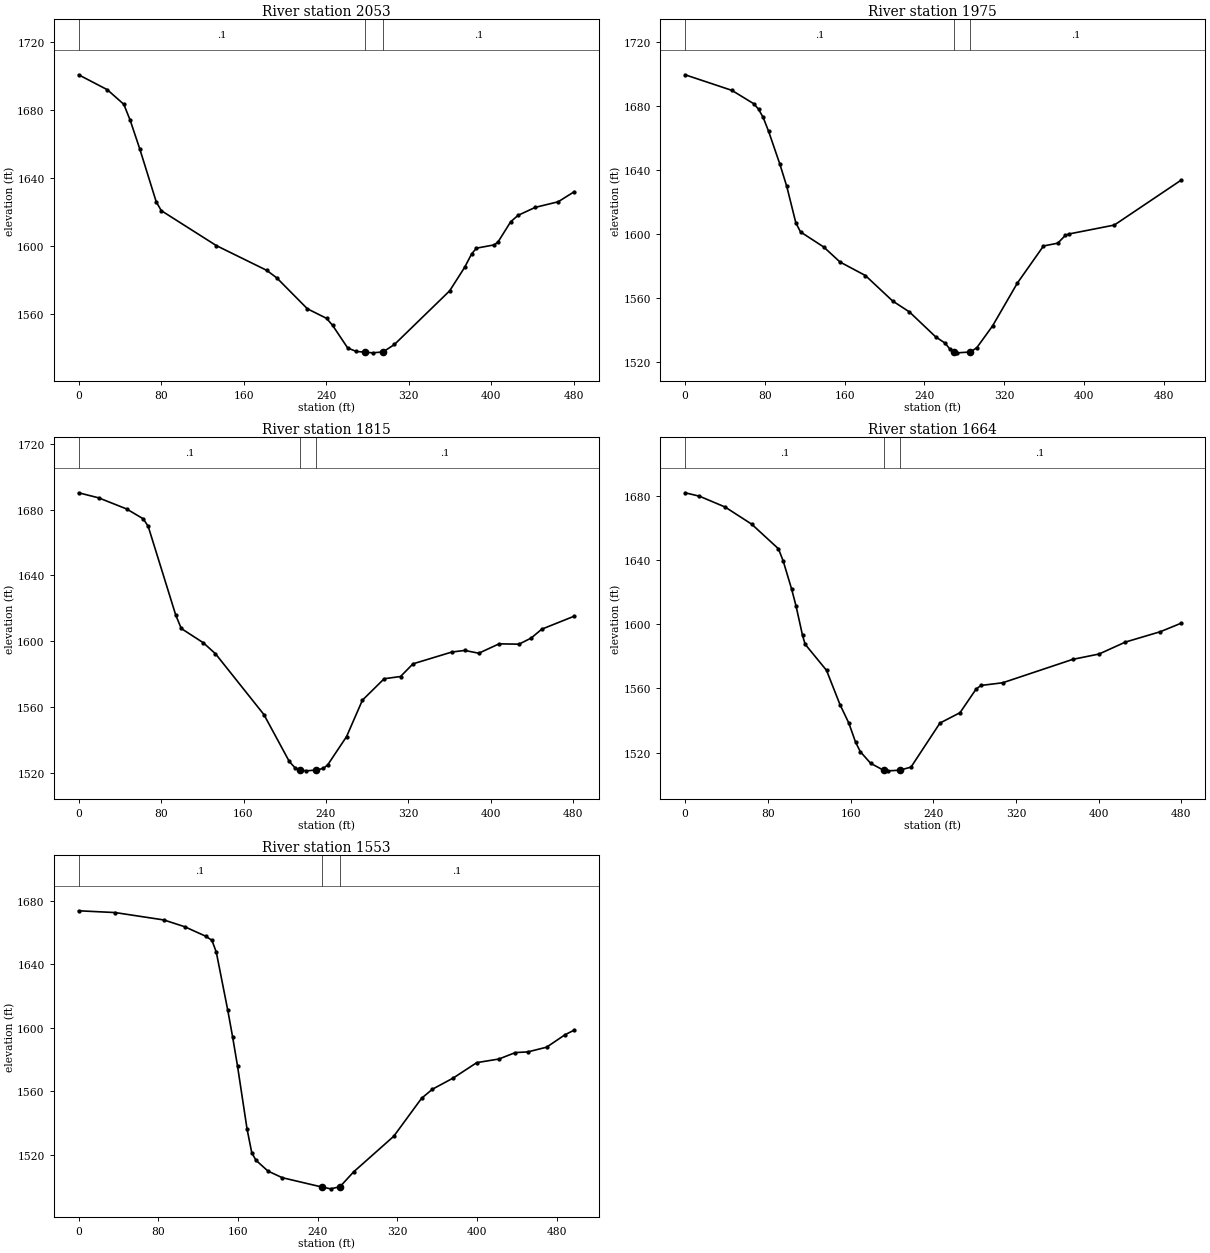
Type RM Length L Ch R = 1 ,2053    ,74.7,77.2,83.4
XS GIS Cut Line= 5
2038442.84573397221647.226661337 2038445.9400728221650.685040032
2038608.98405567221803.0957196692038747.21699767 221907.65653477
2038788.91450644221974.933187569
#Sta/Elev= 30
       0 1700.87    27.8 1692.09    43.8  1683.5      50 1674.06    59.3 1657.19
    75.2 1626.19    80.1 1620.98   133.5 1600.42   182.3 1585.88     192 1581.48
   221.7 1563.28   240.3 1557.65   246.1 1553.57   260.8 1540.21   269.1  1538.2
   277.9 1537.75   284.9 1537.37   295.11537.912   306.1 1542.29   359.6 1573.82
   374.2  1587.7   380.9 1595.55   385.6 1598.92     403 1600.87   406.7 1602.74
   418.7 1614.39   425.9 1618.22   442.6 1622.91   464.8 1626.19   480.3 1632.09
#Mann= 3 ,-1 , 0
       0      .1       0   277.9    .045       0   295.1      .1       0
Bank Sta=277.9,295.1
XS Rating Curve= 0 ,0
Exp/Cntr(USF)=0,0
Exp/Cntr=0.3,0.1

Type RM Length L Ch R = 1 ,1975    ,157.8,160.4,158.4
XS GIS Cut Line= 3
2038393.37384442221678.974251427     2038589.422      221878.168
2038702.80968532222063.584553298
#Sta/Elev= 30
       0 1699.71    46.9 1689.96    68.9 1681.56    73.6 1678.19    78.3 1672.98
    83.7 1664.35      95  1643.8   101.9 1629.91     111 1607.11   115.7 1601.38
     139 1591.93   155.3 1582.55   180.8 1574.07     208 1558.19   224.9 1551.31
   251.3 1535.67   260.7 1531.77   265.4 1528.09   269.71526.277   272.5 1525.71
   286.11526.228   292.5 1528.98   308.2 1542.51   333.1 1569.35   359.3 1592.58
   373.6 1594.33   381.3 1599.24   385.1 1600.12   430.3 1605.67   496.8 1633.56
#Mann= 3 ,-1 , 0
       0      .1       0   269.7    .045       0   286.1      .1       0
Bank Sta=269.7,286.1
XS Rating Curve= 0 ,0
Exp/Cntr(USF)=0,0
Exp/Cntr=0.3,0.1

Type RM Length L Ch R = 1 ,1815    ,150.9,150.9,150.2
XS GIS Cut Line= 2
2038308.45114294221767.5852440912038603.54603675222147.261212088
#Sta/Elev= 30
       0 1690.36    19.4 1687.28    46.5 1680.53    62.7 1674.51    67.5 1669.94
    94.2 1615.97    99.6 1607.73     121 1599.04   132.8 1592.36   179.8 1555.33
   204.4 1526.81     210 1522.92   215.2 1521.57     221 1521.07   230.31521.548
   237.6 1522.56   241.8 1524.78     260 1541.91   275.4 1564.09   296.5 1577.14
   312.4  1578.5   324.5 1586.22   362.3 1593.42   374.7 1594.37   388.3 1592.68
     408 1598.38   427.4 1598.19   439.1 1601.89   449.5 1607.33   480.9 1615.22
#Mann= 3 ,-1 , 0
       0      .1       0   215.2    .045       0   230.3      .1       0
Bank Sta=215.2,230.3
XS Rating Curve= 0 ,0
Exp/Cntr(USF)=0,0
Exp/Cntr=0.3,0.1

Type RM Length L Ch R = 1 ,1664    ,110.5,111.2,108.5
XS GIS Cut Line= 2
2038190.84457139221869.0163121522038495.21200001222239.254417593
#Sta/Elev= 30
       0 1681.99    13.9 1679.85    38.6 1673.14    64.4 1662.43    90.3 1647.08
    94.9 1639.44   103.1 1621.81   107.3 1611.43   113.6 1593.05   116.1 1587.57
   136.8 1571.29   149.8 1549.95   158.3 1538.52   164.9  1526.5   169.5 1520.58
   179.5 1513.34   192.41508.877   196.5 1508.66   207.51509.034   218.5 1510.99
   246.5 1538.44   265.9 1544.91   281.4 1559.57   286.1 1561.88   307.2 1563.56
   374.9 1578.14   400.4 1581.48   425.9 1588.93   459.8 1595.42   479.3 1600.56
#Mann= 3 ,-1 , 0
       0      .1       0   192.4    .045       0   207.5      .1       0
Bank Sta=192.4,207.5
XS Rating Curve= 0 ,0
Exp/Cntr(USF)=0,0
Exp/Cntr=0.3,0.1

Type RM Length L Ch R = 1 ,1553    ,130.2,132.3,132.3
XS GIS Cut Line= 4
 2038095.7760831221937.8632628252038153.93632553222007.736331858
2038329.38582884222165.6408848312038433.97026743222300.320585047
#Sta/Elev= 30
       0 1673.53    36.6 1672.41    85.6 1667.75   106.5 1663.48   127.4 1657.57
   133.8 1654.95   138.2 1647.49   149.7 1611.01   154.6 1594.09   159.5 1575.84
   169.1 1536.09   173.8 1521.27     178 1516.48   190.1 1509.66   204.4 1505.51
   243.91499.666     253 1498.48   262.41499.823   276.1 1509.17   316.4  1531.6
   344.3 1555.48   355.2  1561.2   376.3 1568.32   399.7 1577.93   421.9  1580.2
   438.5 1584.27     451 1584.69   469.8 1587.65   488.3 1595.49   497.5 1598.38
#Mann= 3 ,-1 , 0
       0      .1       0   243.9    .045       0   262.4      .1       0
Bank Sta=243.9,262.4
XS Rating Curve= 0 ,0
Exp/Cntr(USF)=0,0
Exp/Cntr=0.3,0.1