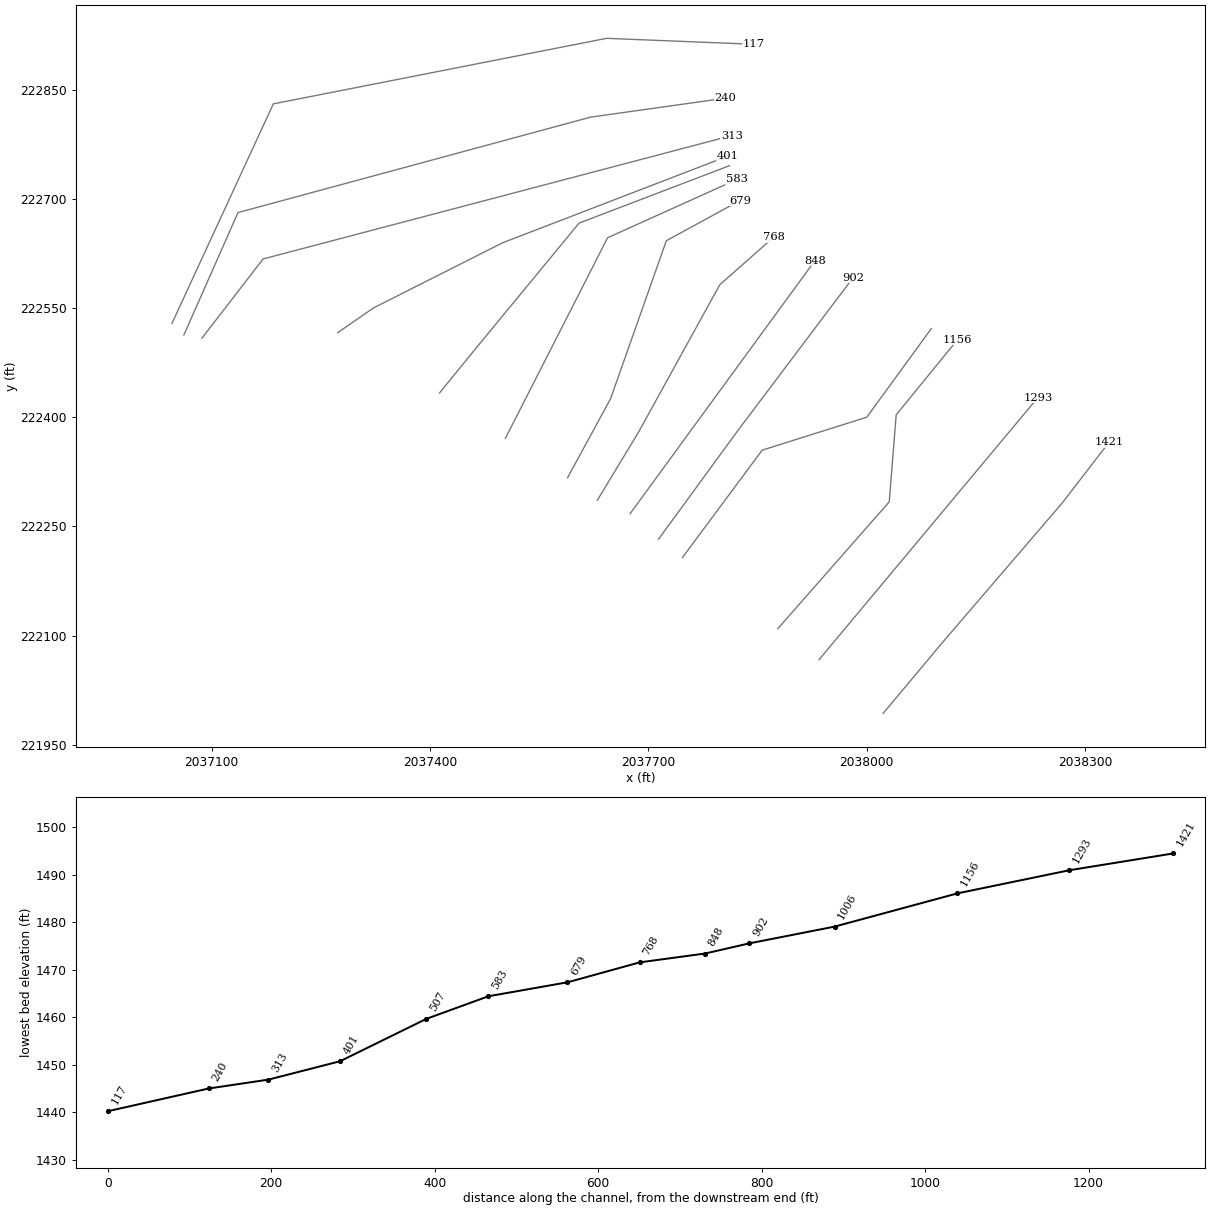
HEC-RAS study STONYCK.prj: STONYCK

--- STONYCK.g01 (geometry) --- (continued)

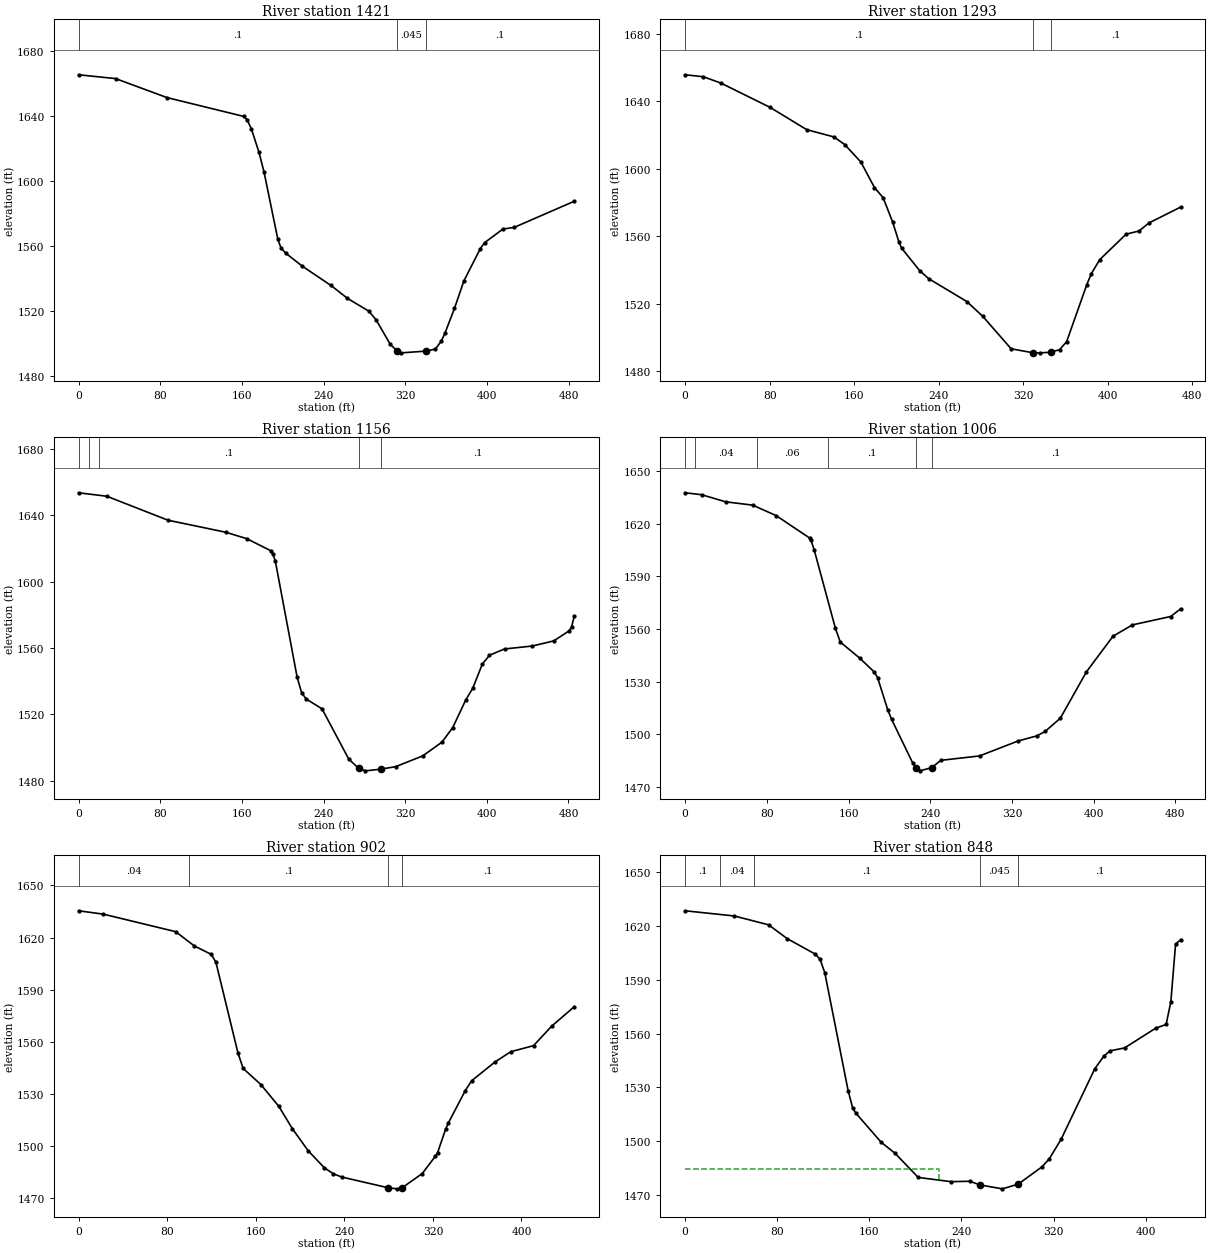
Type RM Length L Ch R = 1 ,1421    ,125.5,127.3,126.4
XS GIS Cut Line= 4
2038022.72105473221993.0471823682038104.49146551222090.676097056
2038268.77600042222282.0755552052038333.43818281222365.948965698
#Sta/Elev= 30
       0 1665.19    36.2 1662.85    86.6 1651.18   161.6 1639.65     165 1637.62
   169.3 1631.92   176.7 1617.56   181.7 1605.33   195.2 1564.07   198.3 1558.88
   202.9 1555.65   219.2 1547.65   247.2 1535.84   263.4 1527.91   284.4 1520.01
   291.4 1514.77   305.3 1499.73     312 1495.61   316.3 1494.46   340.2 1495.51
   349.5 1496.77   355.2 1501.54   358.8 1506.35   368.2  1521.7   377.4 1538.54
   393.5  1558.4   397.7 1562.09   415.7 1570.47   426.7 1571.48   485.5 1587.51
#Mann= 3 ,-1 , 0
       0      .1       0     312    .045       0   340.2      .1       0
Bank Sta=312,340.2
XS Rating Curve= 0 ,0
Exp/Cntr(USF)=0,0
Exp/Cntr=0.3,0.1

Type RM Length L Ch R = 1 ,1293    ,122.6,137,138
XS GIS Cut Line= 2
2037934.79965075222066.9809406212038235.28783163222426.881365087
#Sta/Elev= 30
       0 1655.57    17.3  1654.4    33.9 1650.65    80.2 1636.34   115.1 1623.07
   140.8 1618.77   151.1 1614.24   166.4 1603.84   179.2 1588.78   187.4 1582.79
   196.3  1568.5   202.3 1556.68   204.8 1552.97   221.9 1539.63   230.5 1534.84
   266.6  1521.3   281.8 1512.46   308.5 1493.31   329.4 1490.95   335.4 1490.92
   345.8 1491.26   354.4 1492.81     361  1497.5   380.1 1531.28   384.3 1537.68
   392.3 1546.09   417.3 1561.18   429.6 1563.08   438.9 1567.82   468.9 1577.23
#Mann= 3 ,-1 , 0
       0      .1       0   329.4    .045       0   345.8      .1       0
Bank Sta=329.4,345.8
XS Rating Curve= 0 ,0
Exp/Cntr(USF)=0,0
Exp/Cntr=0.3,0.1

Type RM Length L Ch R = 1 ,1156    ,172.8,150.2,138.6
XS GIS Cut Line= 4
2037877.89217203222109.2807850532038031.12167322 222283.67055069
2038040.69164613222403.2952120332038125.06562766222506.683048554
#Sta/Elev= 30
       0  1653.6    27.6 1651.52    87.5 1637.09   144.3  1629.8   164.8 1625.94
   188.2 1618.71   190.4 1616.58   192.7 1612.61   214.1 1542.53   218.5 1533.14
     223 1529.34   238.5 1523.42   264.7 1493.14   274.5 1487.51   281.1 1486.05
   295.91487.029   310.7 1488.58   337.1 1495.02     356 1503.31   366.6 1512.13
   379.3 1528.69   386.3 1535.94   395.6 1550.35   402.6 1555.71   417.4  1559.5
   444.6 1561.26   465.6 1564.35   480.9 1570.49   483.1 1572.88   485.6 1579.08
#Mann= 5 ,-1 , 0
       0      .1       0      10     .06       0      20      .1       0
   274.5    .045       0   295.9      .1       0
Bank Sta=274.5,295.9
XS Rating Curve= 0 ,0
Exp/Cntr(USF)=0,0
Exp/Cntr=0.3,0.1

Type RM Length L Ch R = 1 ,1006    ,90.2,104.2,113.4
XS GIS Cut Line= 4
  2037746.988224222207.219141861 2037856.5307827222354.707815668
2038000.27728933222399.997810908  2038088.922493222521.788612475
#Sta/Elev= 30
       0 1637.64    16.3 1636.53    39.7 1632.48    66.1  1630.6      89 1624.67
   121.8 1611.88   123.3 1610.48   126.5 1604.79   147.2 1560.24   151.9 1552.51
     171 1543.31     185 1535.53   188.4 1532.27   198.3 1514.02   202.2 1508.38
   222.8 1483.54  225.77 1480.86   229.7 1479.06   241.41480.867   250.3 1485.05
   288.2 1487.55     326 1496.09   344.3    1499   352.4  1501.5   367.3 1509.05
   392.9 1535.54   418.9 1555.83   437.9  1562.3   475.3 1567.07   485.1 1571.44
#Mann= 6 ,-1 , 0
       0     .06       0      10     .04       0      70     .06       0
     140      .1       0  225.77    .045       0   241.4      .1       0
Bank Sta=225.77,241.4
XS Rating Curve= 0 ,0
Exp/Cntr(USF)=0,0
Exp/Cntr=0.3,0.1

Type RM Length L Ch R = 1 ,902     ,53.8,54.2,54.4
XS GIS Cut Line= 4
2037714.09493021  222232.35001442037823.77226023222382.560270734
2037975.29683126222583.5297017912037981.24673763222591.483148055
#Sta/Elev= 30
       0 1635.38    22.4 1633.43    87.6 1623.38   104.5 1615.17   119.9 1610.29
     124 1605.78   143.9 1553.68   148.6 1544.76   164.6  1535.5   180.9 1522.88
   193.1 1510.08   207.3 1497.47   221.9 1487.67   230.1 1484.17   237.7 1482.33
   279.4 1476.18   287.6 1475.54   291.91476.021   310.4 1484.34   322.1 1494.17
   324.2 1496.31   331.4 1509.69   333.8 1513.22   349.3 1532.06   354.9 1537.62
   375.9 1548.38   390.3 1554.36   410.9 1557.85   427.3 1569.07   447.6 1580.19
#Mann= 4 ,-1 , 0
       0     .04       0     100      .1       0   279.4    .045       0
   291.9      .1       0
Bank Sta=279.4,291.9
XS Rating Curve= 0 ,0
Exp/Cntr(USF)=0,0
Exp/Cntr=0.3,0.1

Type RM Length L Ch R = 1 ,848     ,77.5,79.9,81.8
XS GIS Cut Line= 2
  2037674.991285222267.3573627392037928.79975599222614.896025273
#Sta/Elev= 30
       0 1628.61    42.8  1625.7    72.5 1620.77    88.8 1613.02   113.1 1604.41
   117.2 1601.56   121.3 1594.12   141.6 1528.22   145.6 1518.41   148.5 1515.51
   170.3 1499.39   182.1 1493.39   202.5 1479.77     231  1477.4   247.2 1477.63
   256.51475.524   275.6  1473.4   289.31476.009   309.9 1485.65   316.3 1490.15
   326.6 1501.07   355.8 1540.38   363.7 1547.49   369.1 1550.43   381.7 1552.05
   408.9 1563.14   417.8 1565.14   421.9 1577.88     426 1609.98   430.4 1612.45
#Mann= 5 ,-1 , 0
       0      .1       0      30     .04       0      60      .1       0
   256.5    .045       0   289.3      .1       0
#XS Ineff= 2 , 0
          220.39 1484.41
Permanent Ineff=
       F       F
Bank Sta=256.5,289.3
XS Rating Curve= 0 ,0
Exp/Cntr(USF)=0,0
Exp/Cntr=0.3,0.1

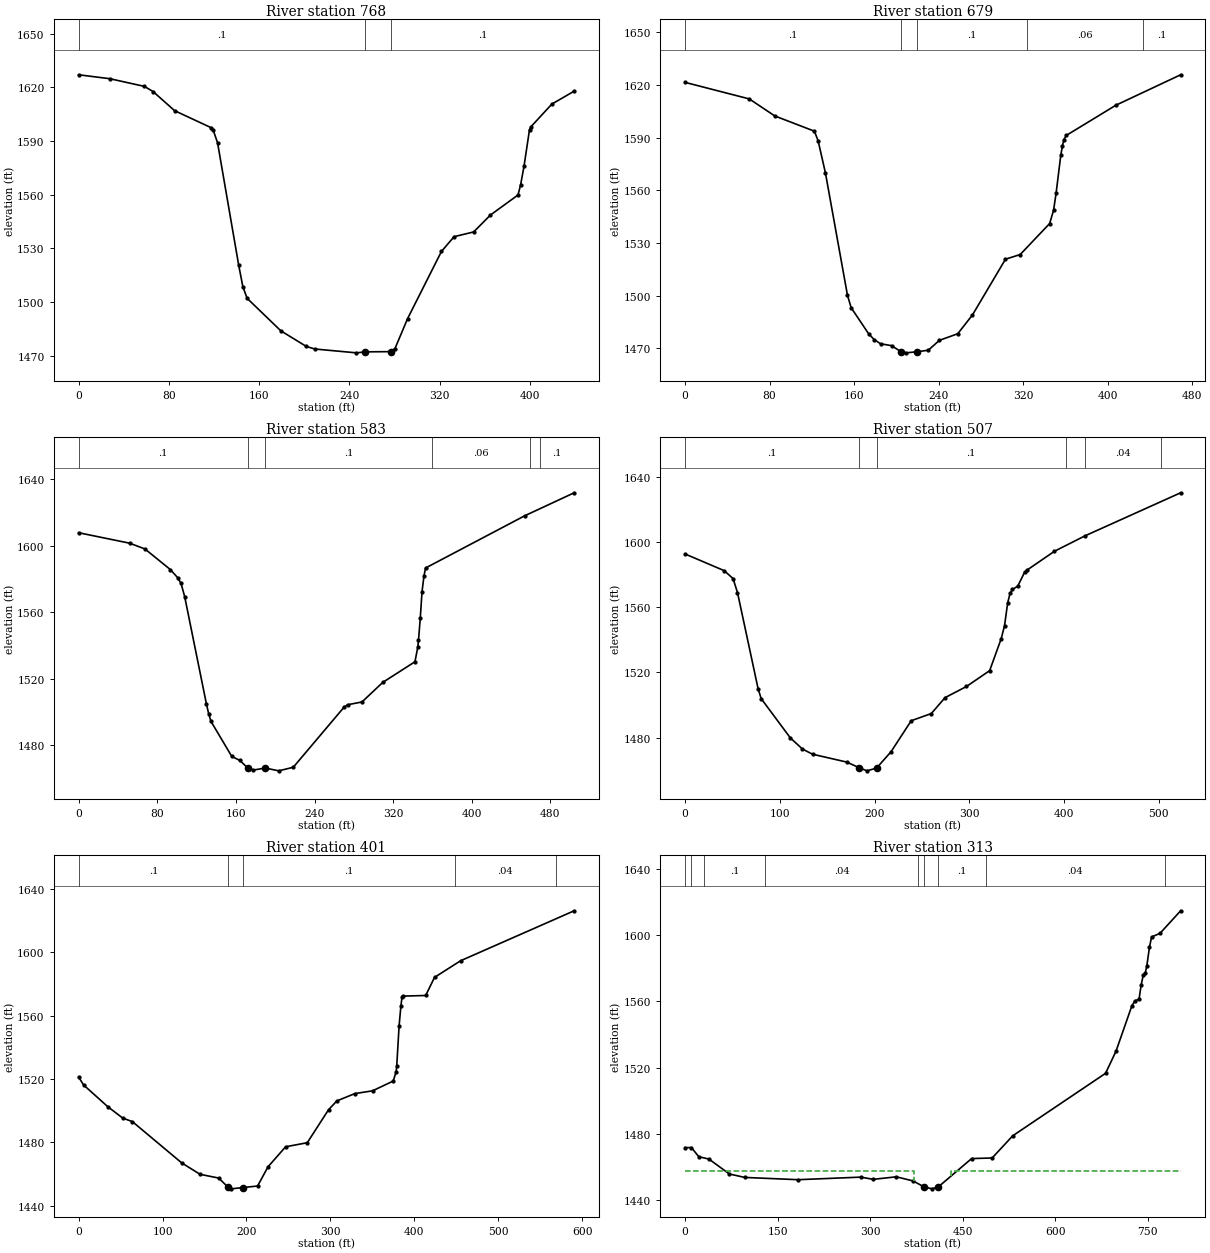
Type RM Length L Ch R = 1 ,768     ,85.1,88.6,90.3
XS GIS Cut Line= 4
2037630.01730747222285.8996793232037686.60264855222379.370279765
2037798.25233247222581.9347063062037872.29351419222647.397946239
#Sta/Elev= 30
       0 1627.03    27.7 1624.83    58.3 1620.54      66 1617.66    85.1 1606.96
   117.2 1597.53   119.4 1595.92   123.2 1588.98   141.9 1520.65   145.6 1508.59
   149.4 1502.02   179.3 1483.85   201.8 1475.16   209.3 1473.69   246.3 1471.54
   254.3 1472.09   276.81472.216   280.5 1473.93   291.7 1490.69   321.7 1528.22
   332.9 1536.49   350.3 1539.15   365.2 1548.63   389.6  1559.8   391.9 1565.47
   394.9 1575.79   399.8 1596.36   401.2 1598.05   419.6 1610.64   439.4 1617.87
#Mann= 3 ,-1 , 0
       0      .1       0   254.3    .045       0   276.8      .1       0
Bank Sta=254.3,276.8
XS Rating Curve= 0 ,0
Exp/Cntr(USF)=0,0
Exp/Cntr=0.3,0.1

Type RM Length L Ch R = 1 ,679     ,98.3,96.6,94.2
XS GIS Cut Line= 4
2037589.19394869222316.9191090712037648.32275692222425.625148817
2037724.88254018 222642.544534722037826.14507396222697.735015216
#Sta/Elev= 30
       0 1621.51    60.8 1612.07    84.9 1602.37   122.4 1593.69   125.9 1588.26
   132.8 1570.03   153.7 1500.17   157.2 1493.06   173.7 1478.24   178.9 1474.94
     185  1472.5   195.4 1471.44   204.61467.917   209.4 1467.34   219.31467.943
   230.2 1468.83   240.7 1474.45   258.1 1478.23     272 1488.91   303.3 1520.72
   317.2 1523.37   345.1 1541.04   348.8 1548.58   351.2 1558.27   355.6 1579.83
   357.2 1585.35   358.6 1588.92     361 1591.33   407.9 1608.52   469.1 1625.84
#Mann= 5 ,-1 , 0
       0      .1       0   204.6    .045       0   219.3      .1       0
  323.75     .06       0  433.78      .1       0
Bank Sta=204.6,219.3
XS Rating Curve= 0 ,0
Exp/Cntr(USF)=0,0
Exp/Cntr=0.3,0.1

Type RM Length L Ch R = 1 ,583     ,79.9,76,71.4
XS GIS Cut Line= 3
 2037503.6564308222370.852935362     2037644.134      222646.606
2037821.66624809222726.633417596
#Sta/Elev= 30
       0 1607.87    51.8 1601.58    67.4 1598.12    93.3 1585.69   100.6 1580.89
   104.2 1577.34   107.9 1569.38     130 1504.77   132.3 1498.88   134.7 1494.17
   155.8 1473.11     164  1470.7   171.9 1466.22   177.9  1464.9     1901466.089
   203.6 1464.41   218.4 1466.57   269.9 1502.65   273.6 1504.22   288.3 1505.91
   309.5 1517.72   342.2 1530.13   345.1 1539.04   345.8 1542.95   347.6 1556.35
   349.4 1572.39   351.4 1581.91     353 1586.62   453.8 1618.06   504.2 1631.94
#Mann= 6 ,-1 , 0
       0      .1       0   171.9    .045       0     190      .1       0
  359.47     .06       0  459.47     .04       0  469.47      .1       0
Bank Sta=171.9,190
XS Rating Curve= 0 ,0
Exp/Cntr(USF)=0,0
Exp/Cntr=0.3,0.1

Type RM Length L Ch R = 1 ,507     ,110.9,105.6,95.3
XS GIS Cut Line= 4
2037413.28372043222433.4361202482037462.96564482222494.409391097
2037604.92024294 222666.668903432037811.58266006222745.602465524
#Sta/Elev= 30
       0 1592.57    41.3 1582.35    50.6 1577.51    55.3 1568.94    77.1 1509.89
    80.3 1503.93   111.1 1479.84   123.9 1473.01   134.5 1469.84   170.7 1465.01
   183.4 1461.67   191.9 1459.65   202.1 1461.32   217.4 1471.37   238.7 1490.37
   259.9 1494.77   274.4 1504.51     297 1511.35   321.5 1521.07   333.7 1540.68
   337.2 1548.63   340.5 1562.56     343 1568.38   345.6 1570.81   351.2 1572.91
   358.3  1581.3   360.8 1582.65   389.9 1594.24   421.8  1603.6   523.1 1630.09
#Mann= 6 ,-1 , 0
       0      .1       0   183.4    .045       0   202.1      .1       0
  401.87     .06       0  421.87     .04       0  501.87      .1       0
Bank Sta=183.4,202.1
XS Rating Curve= 0 ,0
Exp/Cntr(USF)=0,0
Exp/Cntr=0.3,0.1

Type RM Length L Ch R = 1 ,401     ,89.3,87.8,86.3
XS GIS Cut Line= 4
2037273.25403472222516.1578469542037322.60604218222550.234233057
2037499.65054096222639.5539801922037809.63110232222758.896496318
#Sta/Elev= 30
       0 1521.34     5.9 1516.34    34.7 1502.63    52.4 1495.46    64.1 1493.16
   122.8 1467.12   144.7  1459.9   166.9 1457.54     178 1451.79   181.6 1450.73
   196.4 1451.56   213.2 1452.53   225.7 1464.69   246.6 1477.29   272.4 1479.86
   297.7 1500.64   307.6 1506.26   329.1 1510.88   350.2 1512.64   374.8 1518.81
   378.3 1524.69     379 1528.33   381.8 1553.56     384 1566.49   385.3  1571.7
   386.6 1572.46   413.5 1572.85     424 1584.27   455.1 1594.79   590.4 1626.35
#Mann= 5 ,-1 , 0
       0      .1       0     178    .045       0   196.4      .1       0
  448.27     .04       0  568.27      .1       0
Bank Sta=178,196.4
XS Rating Curve= 0 ,0
Exp/Cntr(USF)=0,0
Exp/Cntr=0.3,0.1

Type RM Length L Ch R = 1 ,313     ,75.5,72.9,164
XS GIS Cut Line= 3
2037086.66363103222508.5046180942037170.72772299222617.427599014
2037814.69504813222786.953535646
#Sta/Elev= 30
       0 1471.73    10.2 1471.78    22.2 1466.26    38.7 1464.82    71.9  1455.8
    96.8 1453.75   183.1 1452.38   284.8 1453.93   305.2  1452.6   342.5 1454.12
   369.7 1451.64   386.6 1448.19   400.2 1446.86   410.4 1447.97   464.6 1465.13
   497.9 1465.49   531.2 1478.87   681.8  1516.6   698.7 1529.95   724.5 1557.42
   729.3  1560.2   736.1 1561.49   739.4 1569.73   742.8 1575.73   746.2 1577.25
   748.7 1581.53     753 1592.84   756.4  1598.9     770 1601.06   803.5  1614.7
#Mann= 9 ,-1 , 0
       0     .06       0      10     .04       0      30      .1       0
     130     .04       0  377.59      .1       0   386.6    .045       0
   410.4      .1       0  487.59     .04       0  777.59      .1       0
#XS Ineff= 2 , 0
          370.82 1457.86  431.17         1457.86
Permanent Ineff=
       F       F
Bank Sta=386.6,410.4
XS Rating Curve= 0 ,0
Exp/Cntr=0.5,0.3

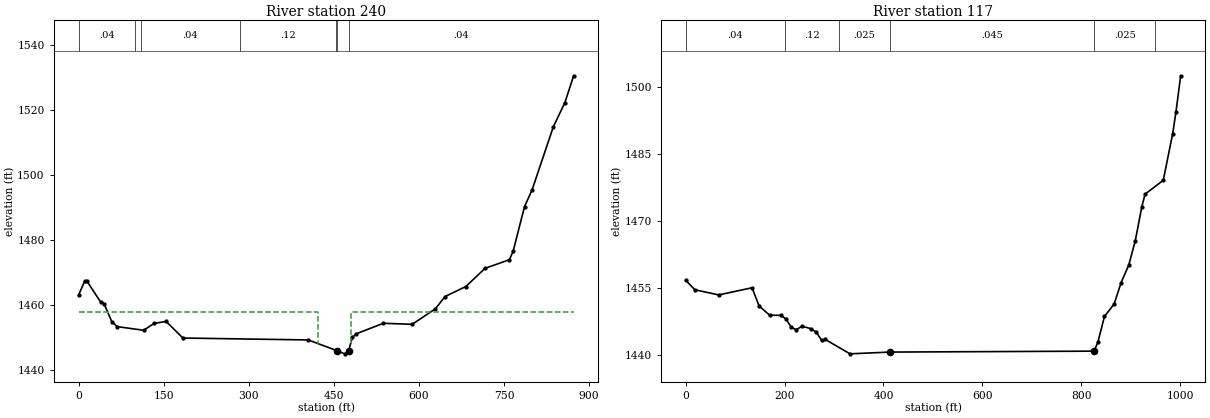
Type RM Length L Ch R = 1 ,240     ,152.1,123.5,221.5
XS GIS Cut Line= 4
2037061.89666041222512.9415452352037136.27742921222681.160642495
     2037620.645      222812.2892037805.70575924222838.304762427
#Sta/Elev= 30
       0 1463.15    10.7 1467.36    14.3 1467.48    38.7 1461.02    45.2 1460.32
    58.6 1454.87    68.1 1453.38   114.8 1452.26   132.7 1454.35   154.2 1454.99
   183.9 1449.87   404.9 1449.28   456.31445.907   469.1    1445   475.9 1445.92
   482.7 1450.11   489.5 1451.17   537.1 1454.41   588.1  1454.1   628.9 1458.87
   645.9 1462.65   682.6 1465.74   716.4 1471.33   759.5 1474.01   766.1  1476.7
     786 1490.34   799.3 1495.49   836.8 1514.94   857.2 1522.42   872.6 1530.66
#Mann= 7 ,-1 , 0
       0     .04       0     100      .1       0     110     .04       0
  283.93     .12       0  453.93     .04       0   456.3    .045       0
   475.9     .04       0
#XS Ineff= 2 , 0
             422 1457.86     480         1457.86
Permanent Ineff=
       F       F
Bank Sta=456.3,475.9
XS Rating Curve= 0 ,0
Exp/Cntr=0.5,0.3

Type RM Length L Ch R = 1 ,117     ,,,
XS GIS Cut Line= 4
2037045.53647408222528.8612705472037184.81479916 222830.53239134
2037642.71410471222920.5931552052037844.35639467222912.462417719
#Sta/Elev= 30
       01456.718  18.5821454.555  67.0041453.406 134.2181455.005 148.6731450.907
 169.8491448.863 192.235 1448.83 202.8771448.022 213.7181446.134 223.5431445.634
   235.41446.378 253.4681445.849 264.3091445.036  275.15  1443.2 282.3771443.433
 332.2711440.214 412.882 1440.61  825.871440.819 833.5531442.902 846.6871448.582
 866.3881451.378 880.3681456.177 895.9391460.113 909.0731465.568 922.2071473.105
 928.7741475.961 965.5871479.063 984.594  1489.5 991.1611494.3011000.7491502.457
#Mann= 6 ,-1 , 0
       0     .04       0     200     .12       0     310    .025       0
 412.882    .045       0  825.87    .025       0  948.94     .04       0
Bank Sta=412.882,825.87
XS Rating Curve= 0 ,0
Exp/Cntr(USF)=0,0
Exp/Cntr=0.3,0.1
LCMann Table=0

Chan Stop Cuts=-1
Use User Specified Reach Order=0
Composite Channel Slope=5